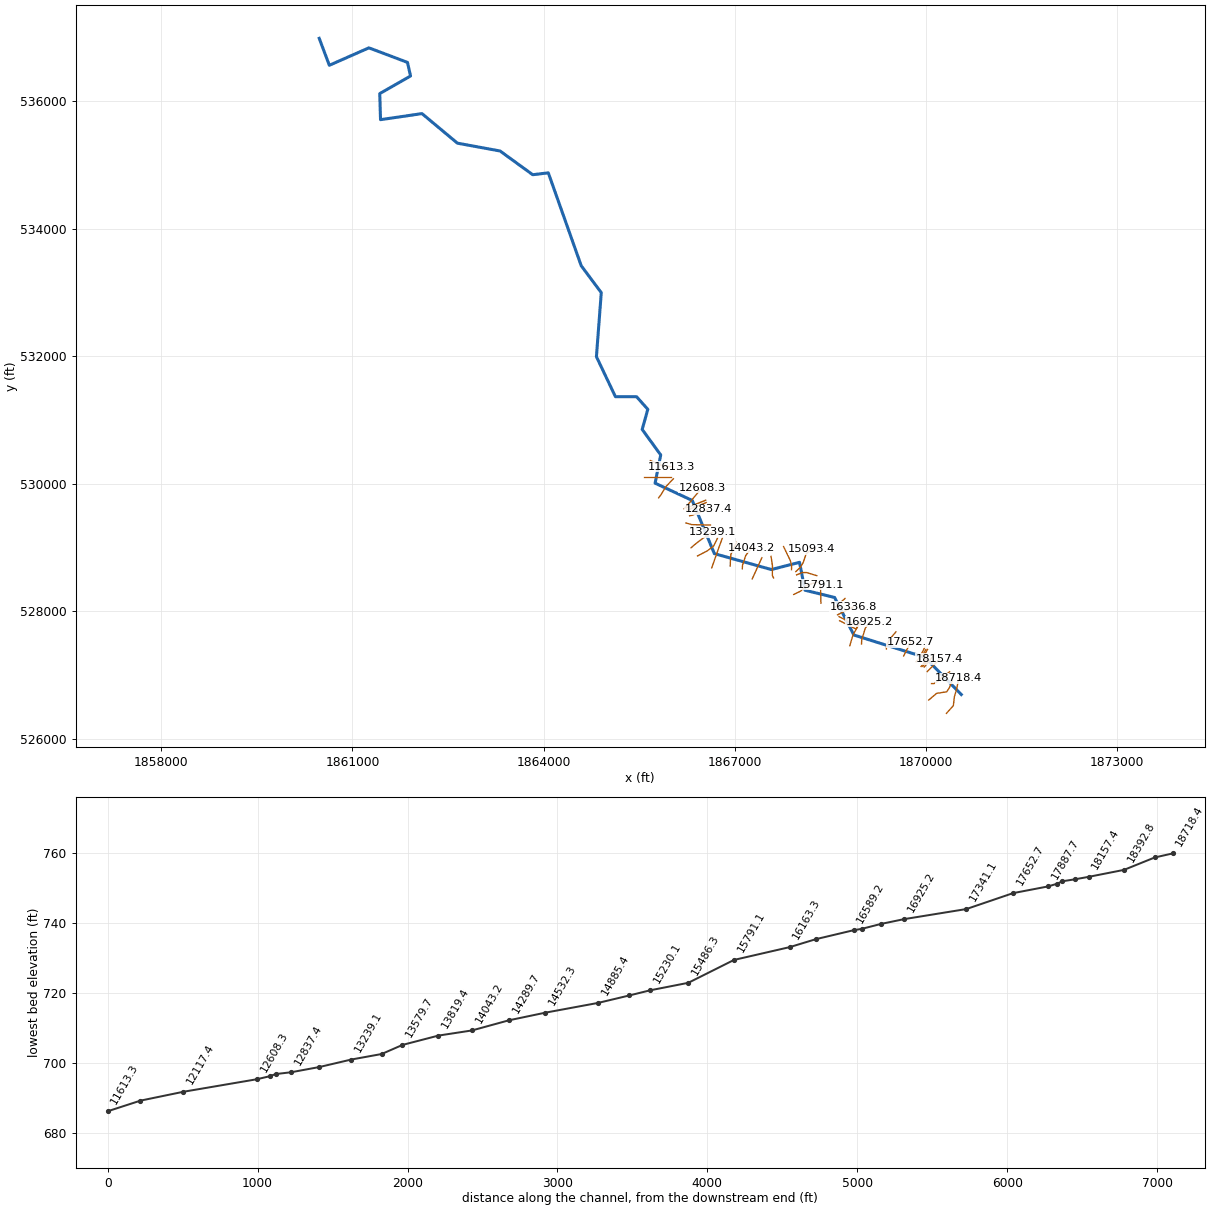
--- LEATHRWDFK.prj (project) ---

Proj Title=LEATHRWDFK
Current Plan=p01
Default Exp/Contr=0,0
English Units
Geom File=g01
Flow File=f01
Plan File=p01
BEGIN DESCRIPTION:
END DESCRIPTION:
DSS Export Rating Curves= 0
DSS Export Rating Curve Sorted= 0
DSS Export Volume Flow Curves= 0
DXF OffsetX= 0
DXF OffsetY= 0
DXF ScaleX= 0
DXF ScaleY= 0

--- LEATHRWDFK.p01 (plan) ---

Plan Title=Floodplain
Program Version=4.00
Geom File=g01
Flow File=f01
K Sum by GR=0
Std Step Tol=0.01
Critical Tol=0.01
Num of Std Step Trials=20
Max Error Tol=0.3
Flow Tol Ratio=0.001
Split Flow NTrial=30
Split Flow Tol=0.02
Split Flow Ratio=0.02
Log Output Level=0
Friction Slope Method=1
Unsteady Friction Slope Method=2
Unsteady Bridges Friction Slope Method=1
Global Log Level=0
CheckData=False
Run HTab=0
Run UNet=0
Run PostProcess=0
UNET Theta=0
UNET Theta Warmup=0
UNET ZTol=0
UNET ZSATol=0
UNET MxIter=0
UNET MaxInSteps=0
UNET DtIC=0
UNET DtMin=0
UNET MaxCRTS=0
UNET WFStab=0
UNET SFStab=0
UNET WFX=0
UNET SFX=0
UNET DSS MLevel=0
UNET DZMax Abort=0
UNET Convert EG Bridges=0
UNET Use Existing IB Tables=0
UNET Froude Limit=0
UNET Froude Power=0
Write IC File=0
Echo Input=False
Echo Output=False
Write Detailed=0

--- LEATHRWDFK.f01 (steady flow) ---

Flow Title=NFF Regression Equation
Program Version=4.10
Number of Profiles= 1
Profile Names=P100yr
River Rch & RM=LEATHRWDFK,Main            ,18718.4
851.9405
River Rch & RM=LEATHRWDFK,Main            ,18157.4
1020.066
River Rch & RM=LEATHRWDFK,Main            ,15486.3
 1126.93
River Rch & RM=LEATHRWDFK,Main            ,14532.3
1191.903
River Rch & RM=LEATHRWDFK,Main            ,13239.1
1420.457
River Rch & RM=LEATHRWDFK,Main            ,8888.9
1526.323
River Rch & RM=LEATHRWDFK,Main            ,5861
2278.618
River Rch & RM=LEATHRWDFK,Main            ,810.1
2425.126
Boundary for River Rch & Prof#=LEATHRWDFK,Main            , 1
Up Type= 0
Dn Type= 3
Dn Slope=0.007
DSS Import GetInterval= 0
DSS Import GetPeak= 0
DSS Import FillOption= 0

--- LEATHRWDFK.g01 (geometry) ---

Geom Title=USGS 10m DEM
Program Version=4.10

River Reach=LEATHRWDFK      ,Main
Reach XY= 30
     1870557.722      526694.197     1869986.504      527277.507
     1868871.052      527627.985     1868569.057        528216.3
     1868103.908      528330.024     1868018.347      528767.547
     1867575.639      528654.265     1866681.107      528904.265
     1866334.753      529737.599     1865751.202      530008.835
     1865839.368      530451.335      1865548.57      530851.726
     1865636.837      531167.286     1865460.541      531364.666
     1865128.648      531364.964     1864830.254      531993.219
     1864906.368      532996.713     1864591.538         533419.
     1864074.865      534876.226     1863830.387      534846.669
     1863318.029      535218.624     1862648.095      535341.461
     1862092.106      535805.002     1861441.292      535709.943
     1861429.345      536118.804     1861912.418      536394.846
     1861864.241      536608.388     1861258.772      536836.252
     1860637.679      536562.815     1860478.818      536985.528

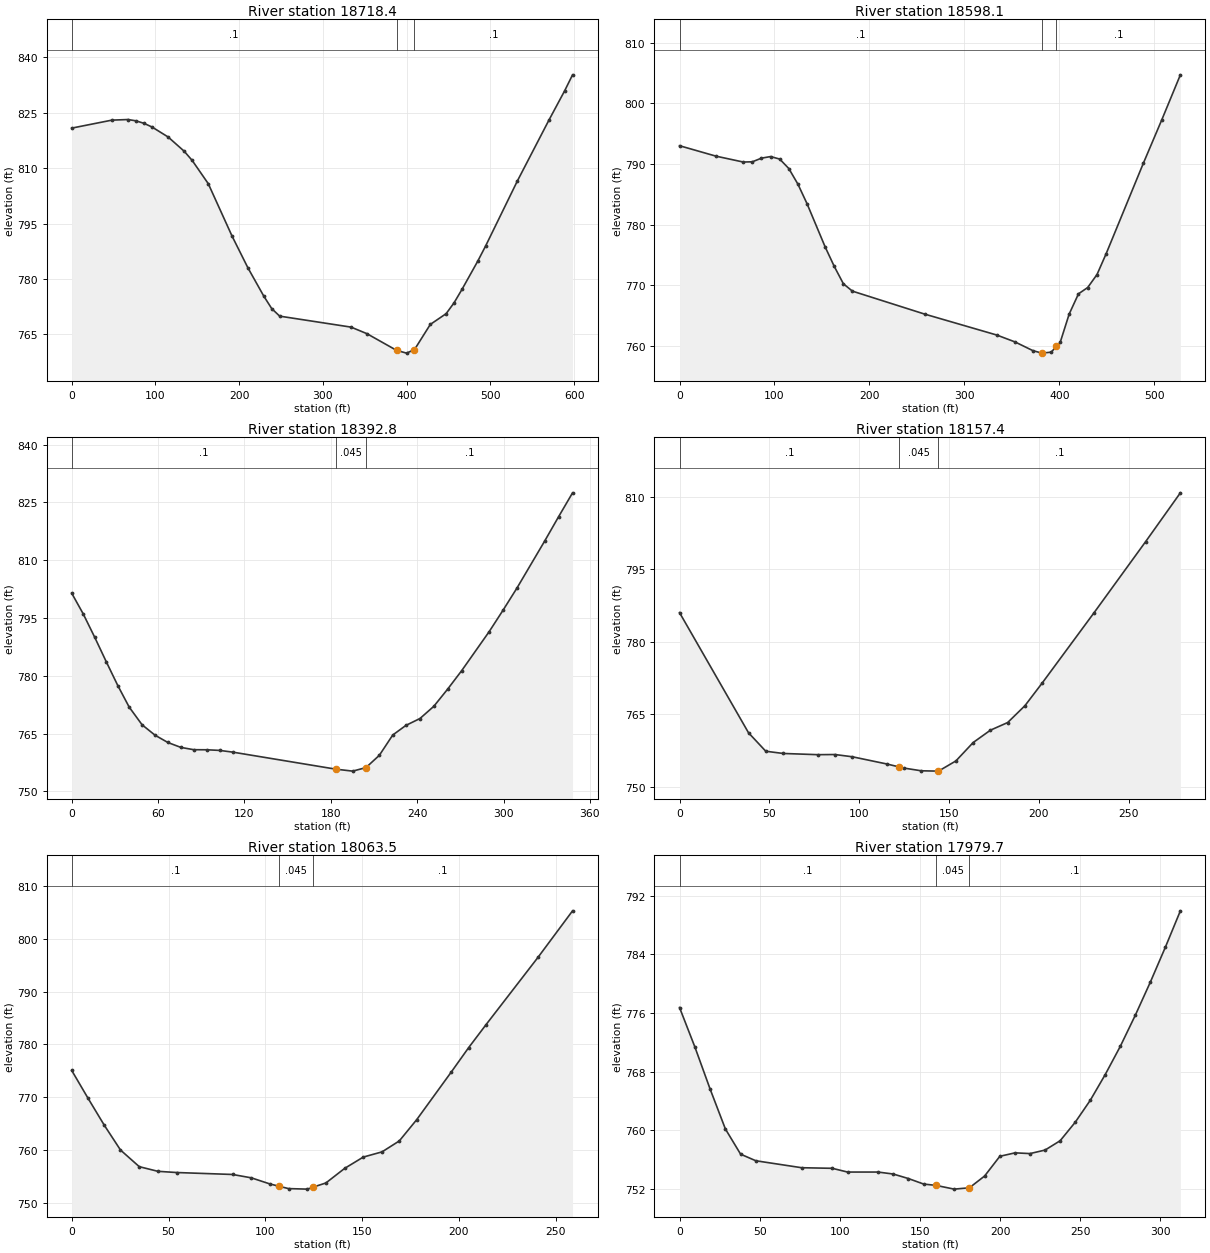
Type RM Length L Ch R = 1 ,18718.4 ,126.2,120.2,114.4
XS GIS Cut Line= 5
     1870323.946      526398.615     1870433.116      526519.808
     1870449.814      526660.985     1870484.536      526779.041
     1870517.522      526945.707
#Sta/Elev= 30
       0   820.8      48  822.96    67.2  823.12    76.8  822.77    86.4  822.09
      96  821.09   115.1  818.41   134.3  814.56   143.9  812.06   163.1  805.78
   191.5  791.61   210.5     783   229.4  775.38   238.9     772   248.4  769.96
   333.7  766.99   352.6  765.22   388.1   760.7   399.9  759.96   409.4  760.91
   428.3  767.72   447.2  770.63   456.6  773.54   466.1  777.18     485  784.84
   494.4  788.95   532.2  806.47   569.9  822.93   588.8  830.91   598.2  835.21
#Mann= 3 , 0 , 0
       0      .1       0   388.1    .045       0   409.4      .1       0
Bank Sta=388.1,409.4
XS Rating Curve= 0 ,0
Exp/Cntr=0.3,0.1

Type RM Length L Ch R = 1 ,18598.1 ,211.4,205.3,198.7
XS GIS Cut Line= 5
     1870046.168      526606.949     1870170.296      526712.674
     1870330.022      526737.374     1870375.161      526810.291
     1870416.828      526919.666
#Sta/Elev= 30
       0     793    38.4  791.28    67.1  790.31    76.7  790.35    86.3  790.95
    95.9  791.21   105.5   790.8   115.1  789.24   124.7  786.66   134.3  783.44
   153.5  776.27     163  773.09   172.6  770.23   182.1  769.02   258.1  765.24
   334.2  761.78   353.3  760.65   372.3   759.2   381.8   758.8   391.4  758.96
     397   759.9   400.9  760.56   410.4  765.25   420.2  768.58   429.9  769.62
   439.7  771.76   449.4  775.22   488.5  790.11     508   797.3   527.5  804.69
#Mann= 3 , 0 , 0
       0      .1       0   381.8    .045       0     397      .1       0
Bank Sta=381.8,397
XS Rating Curve= 0 ,0
Exp/Cntr=0.3,0.1

Type RM Length L Ch R = 1 ,18392.8 ,234.5,235.4,236.4
XS GIS Cut Line= 5
     1870090.439      526865.846     1870130.369      526865.846
     1870191.133      526904.041     1870281.411      526983.902
     1870375.161       527051.61
#Sta/Elev= 30
       0  801.43       8  796.05      16  789.97      24  783.64      32  777.47
    39.9  771.88    48.9  767.27    57.9  764.57    66.8  762.68    75.8  761.41
    84.8  760.81    93.8  760.79   102.7  760.63   111.7  760.19   183.6  755.75
   195.2  755.25   204.4  756.17   213.7  759.36     223  764.62   232.2  767.13
   241.9   768.9   251.5  772.06   261.1  776.51   270.8  781.28     290  791.46
   299.7  797.06   309.3  802.77   328.6     815   338.2  821.27   347.9  827.47
#Mann= 3 , 0 , 0
       0      .1       0   183.6    .045       0   204.4      .1       0
Bank Sta=183.6,204.4
XS Rating Curve= 0 ,0
Exp/Cntr=0.3,0.1

Type RM Length L Ch R = 1 ,18157.4 ,91.8,93.9,95.9
XS GIS Cut Line= 2
     1870022.731      527053.346     1870218.911      527251.263
#Sta/Elev= 21
       0  786.02    38.4  761.18      48  757.37    57.7  756.91    76.9  756.66
    86.5  756.69    96.1  756.23   115.3  754.74   122.4  754.11   124.9  753.89
   134.5  753.33   144.1  753.26   153.8  755.37   163.4  759.17     173  761.72
   182.6   763.3   192.2  766.78   201.8  771.46   230.6  785.96   259.4   800.7
   278.7  810.77
#Mann= 3 , 0 , 0
       0      .1       0   122.4    .045       0   144.1      .1       0
Bank Sta=122.4,144.1
XS Rating Curve= 0 ,0
Exp/Cntr=0.3,0.1

Type RM Length L Ch R = 1 ,18063.5 ,25.7,83.8,112.9
XS GIS Cut Line= 4
     1869974.924       527124.35     1869991.417      527143.447
     1870077.354      527247.614      1870137.25      527325.739
#Sta/Elev= 25
       0  775.06     8.4   769.8    16.8  764.68    25.2  759.96    34.9   756.8
    44.5  755.92    54.2  755.69    83.1  755.32    92.8  754.68   102.4  753.52
   107.3  753.07     112  752.64   121.7  752.54  124.62  752.91   131.3  753.71
     141  756.48   150.6  758.62   160.3  759.61   169.2  761.68   178.2  765.72
   196.1  774.78     205  779.37     214  783.74   240.8  796.49   258.7  805.34
#Mann= 3 , 0 , 0
       0      .1       0   107.3    .045       0  124.62      .1       0
Bank Sta=107.3,124.62
XS Rating Curve= 0 ,0
Exp/Cntr=0.3,0.1

Type RM Length L Ch R = 1 ,17979.7 ,61.8,30.8,28
XS GIS Cut Line= 4
     1869952.354      527136.503     1870019.195      527217.232
     1869974.924       527311.85     1870027.875      527400.392
#Sta/Elev= 30
       0  776.76     9.5  771.42    19.1  765.62    28.6  760.19    38.1  756.75
    47.6  755.85    76.2   754.9    95.3  754.82   104.8  754.31   123.8  754.31
   133.3  754.04   142.8  753.42   152.3  752.67     160  752.49   171.3  751.98
   180.8  752.16   190.3  753.77   199.8  756.46   209.3  756.93   218.6  756.83
     228  757.31   237.4  758.58   246.8   761.1   256.2   764.1   265.5   767.6
   274.9  771.45   284.3  775.71   293.7  780.24   303.1  785.02   312.4  789.95
#Mann= 3 , 0 , 0
       0      .1       0     160    .045       0   180.8      .1       0
Bank Sta=160,180.8
XS Rating Curve= 0 ,0
Exp/Cntr=0.3,0.1

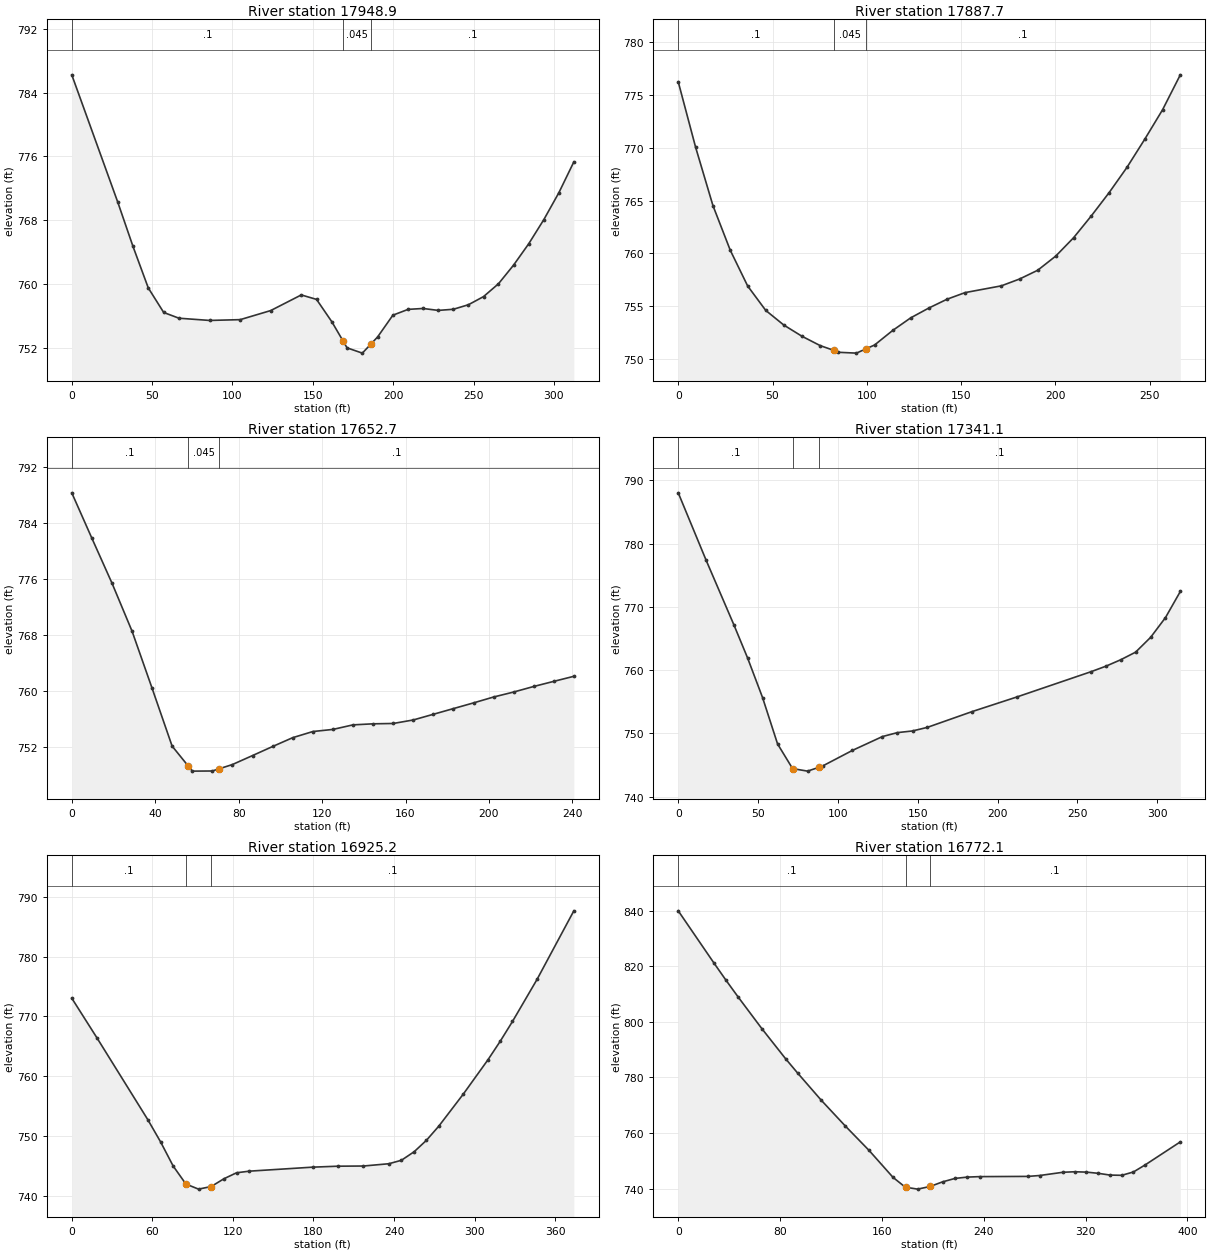
Type RM Length L Ch R = 1 ,17948.9 ,84.5,61.2,38.2
XS GIS Cut Line= 4
     1869926.313      527133.899     1869993.153      527214.628
     1869948.882      527309.246     1870001.834      527397.788
#Sta/Elev= 30
       0  786.23    28.6  770.27    38.1   764.7    47.6   759.5    57.2  756.42
    66.7   755.7    85.8  755.42   104.8  755.52   123.8  756.66   142.8  758.62
   152.3  758.06   161.8  755.26   168.9  752.81   171.3  751.98   180.8  751.32
  186.32   752.5   190.3  753.35   199.8  756.08   209.3  756.81   218.6  756.92
     228  756.68   237.4  756.82   246.8  757.39   256.2  758.41   265.5  760.02
   274.9  762.36   284.3  765.03   293.7  768.06   303.1  771.45   312.4  775.31
#Mann= 3 , 0 , 0
       0      .1       0   168.9    .045       0  186.32      .1       0
Bank Sta=168.9,186.32
XS Rating Curve= 0 ,0
Exp/Cntr=0.3,0.1

Type RM Length L Ch R = 1 ,17887.7 ,233.6,234.9,236.4
XS GIS Cut Line= 4
     1869848.188      527208.552     1869874.229      527234.593
     1869955.827      527376.086     1869983.604      527435.982
#Sta/Elev= 30
       0  776.26     9.2  770.06    18.4  764.52    27.6  760.28    36.8   756.9
    46.4  754.58      56  753.19    65.6  752.13    75.3  751.24   82.37   750.8
    84.9  750.61    94.5  750.53    99.3  750.92   104.1   751.3   113.7  752.68
   123.3  753.88   132.9  754.81   142.5  755.64   152.1  756.27   171.3  756.91
     181  757.56   190.6  758.39   200.2  759.74   209.6  761.47     219  763.54
   228.5  765.76   237.9  768.14   247.3   770.8   256.8  773.61   266.2  776.92
#Mann= 3 , 0 , 0
       0      .1       0   82.37    .045       0    99.3      .1       0
Bank Sta=82.37,99.3
XS Rating Curve= 0 ,0
Exp/Cntr=0.3,0.1

Type RM Length L Ch R = 1 ,17652.7 ,310.3,311.6,312.8
XS GIS Cut Line= 2
     1869652.939      527299.874      1869764.05      527513.416
#Sta/Elev= 28
       0  788.37     9.6  781.91    19.3  775.45    28.9   768.6    38.5  760.45
    48.1  752.18    55.7  749.38    57.8   748.6    67.4  748.62    70.7  748.94
      77  749.54    86.7  750.83    96.3  752.12   105.9  753.38   115.6  754.26
   125.2  754.56   134.8  755.21   144.4  755.36   154.1  755.41   163.7  755.91
   173.3  756.72     183  757.54   192.6  758.35   202.2  759.19   211.8   759.9
   221.5   760.7   231.1  761.43   240.7  762.15
#Mann= 3 , 0 , 0
       0      .1       0    55.7    .045       0    70.7      .1       0
Bank Sta=55.7,70.7
XS Rating Curve= 0 ,0
Exp/Cntr=0.3,0.1

Type RM Length L Ch R = 1 ,17341.1 ,412.4,415.9,418.8
XS GIS Cut Line= 4
     1869382.106      527409.249     1869383.842      527452.652
     1869434.189      527563.763     1869531.411       527676.61
#Sta/Elev= 24
       0  788.05    17.4  777.43    34.8  767.21    43.4  761.96    52.8  755.68
    62.2  748.35    71.6  744.45      81  744.05    87.9  744.64    90.4  744.86
   109.1  747.33   127.9  749.52   137.3  750.14   146.7   750.4     156  750.97
     184  753.46     212  755.77   258.5  759.77   267.8  760.64   277.1  761.66
   286.4  762.86   295.8   765.2   305.1  768.32   314.4  772.45
#Mann= 3 , 0 , 0
       0      .1       0    71.6    .045       0    87.9      .1       0
Bank Sta=71.6,87.9
XS Rating Curve= 0 ,0
Exp/Cntr=0.3,0.1

Type RM Length L Ch R = 1 ,16925.2 ,155.7,153.1,148.9
XS GIS Cut Line= 4
     1868991.481      527487.374     1868994.953      527553.346
     1869050.508      527733.902     1869116.481       527832.86
#Sta/Elev= 25
       0  773.05    18.9  766.37    56.6  752.77    66.1  749.07    75.5  745.02
      85  742.01    94.4  741.16   103.8  741.59   113.3  742.89   122.7  743.89
   132.2  744.16   179.4  744.83   198.3  744.99   217.2  745.02   236.1   745.4
   245.5  745.98     255  747.41   264.1  749.31   273.3  751.67   291.6  757.04
   309.9  762.75     319  765.83   328.2  769.16   346.5  776.19   373.9  787.64
#Mann= 3 , 0 , 0
       0      .1       0      85    .045       0   103.8      .1       0
Bank Sta=85,103.8
XS Rating Curve= 0 ,0
Exp/Cntr=0.3,0.1

Type RM Length L Ch R = 1 ,16772.1 ,167.1,129.4,93.4
XS GIS Cut Line= 4
     1868807.713      527459.466     1868855.176      527621.312
     1868896.562      527698.572     1868964.898      527818.534
#Sta/Elev= 30
       0  839.93    28.1  821.12    37.5  814.97    46.8  809.09    65.6  797.59
    84.3  786.74    93.7  781.61   112.4  771.76   131.2  762.53   149.9  753.73
   168.7  744.04   178.4  740.49   179.1  740.44   188.1   739.8   197.9  740.76
   207.6  742.41   217.4  743.65   227.1  744.13   236.8   744.3   274.7  744.38
   283.9   744.7   302.3  745.87   311.5  746.05   320.7  745.92   329.9  745.49
   339.1  744.86   348.4  744.77   357.6  745.98   366.8  748.52   394.4   756.8
#Mann= 3 , 0 , 0
       0      .1       0   179.1    .045       0   197.9      .1       0
Bank Sta=179.1,197.9
XS Rating Curve= 0 ,0
Exp/Cntr=0.3,0.1

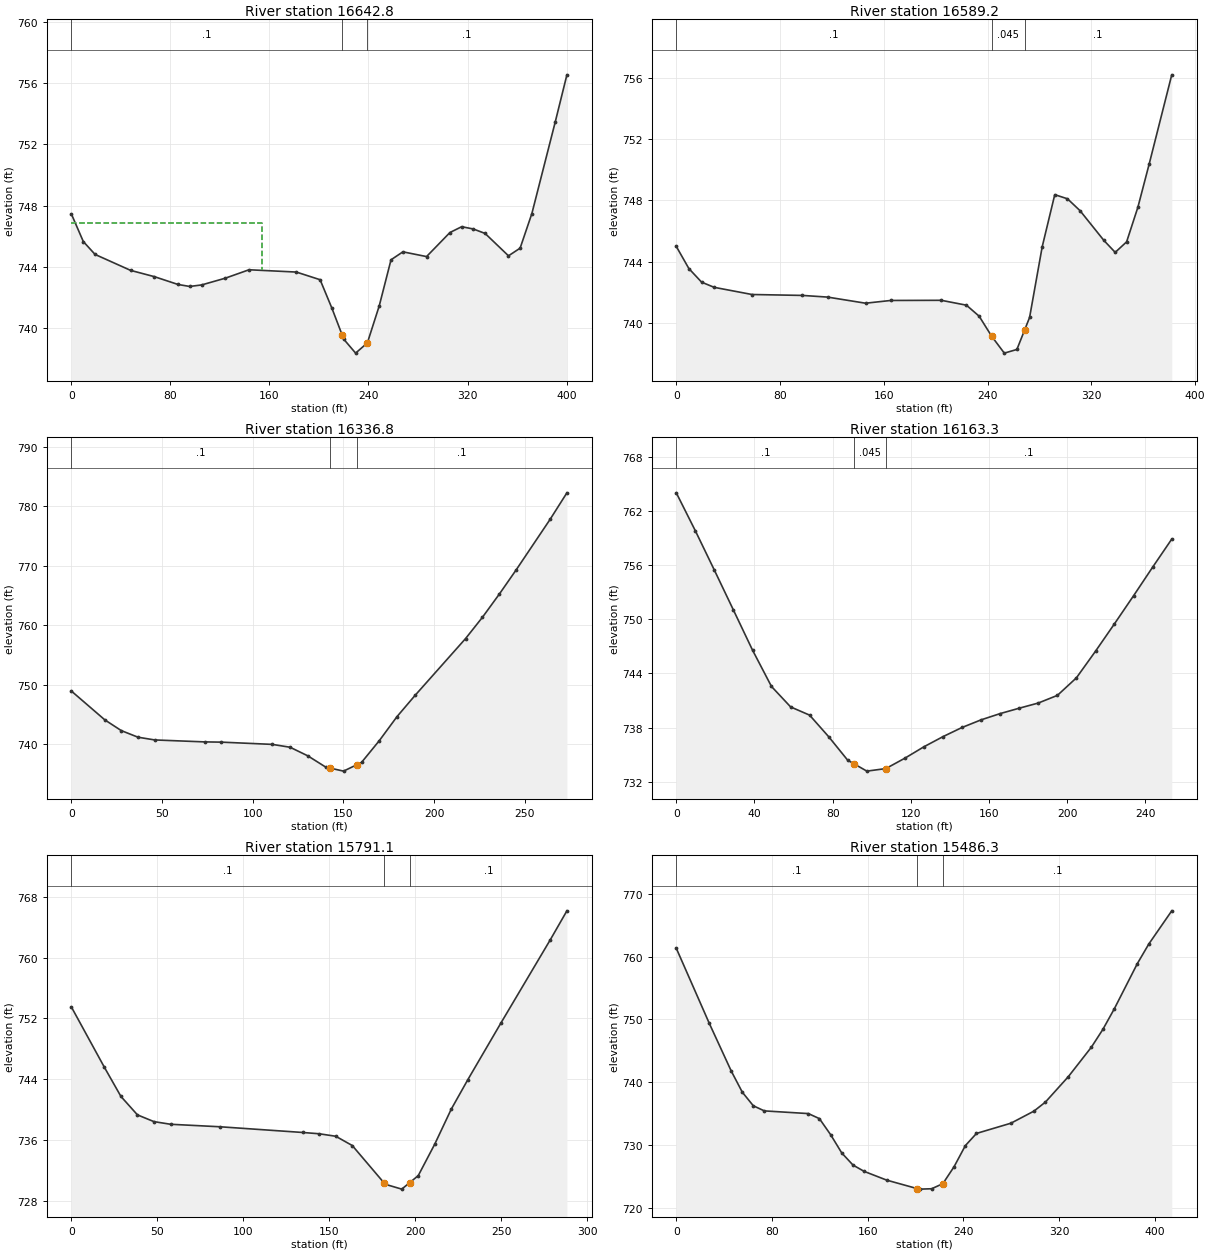
Type RM Length L Ch R = 1 ,16642.8 ,54,53.5,53.3
XS GIS Cut Line= 3
     1868647.731      527851.957     1868903.395      527721.683
     1868956.564       527821.79
#Sta/Elev= 30
       0  747.45     9.6  745.66    19.1  744.82    47.8  743.78      67  743.37
    86.1  742.86    95.6  742.73   105.2  742.83   124.3  743.27   143.5  743.82
   181.7  743.67   200.9  743.17   210.4  741.32   218.6  739.59     220  739.29
   229.6  738.38   239.1  739.05   248.7  741.47   258.2  744.47   267.8  744.99
   286.9  744.68   305.8  746.25   315.3  746.63   324.7  746.48   334.2  746.19
   353.1  744.73   362.5  745.23     372  747.49   390.8  753.44   400.3  756.54
#Mann= 3 , 0 , 0
       0      .1       0   218.6    .045       0   239.1      .1       0
#XS Ineff= 2 , 0
          153.68  746.86
Permanent Ineff=
       F       F
Bank Sta=218.6,239.1
XS Rating Curve= 0 ,0
Exp/Cntr=0.3,0.1

Type RM Length L Ch R = 1 ,16589.2 ,229.1,252.4,274.9
XS GIS Cut Line= 3
     1868637.748      527915.976     1868923.556       527769.82
     1868951.877      527823.873
#Sta/Elev= 27
       0  744.99     9.7  743.54    19.5  742.65    29.2  742.31    58.4  741.84
    97.3  741.78   116.7  741.67   145.9  741.27   165.4  741.45   204.3  741.46
   223.7  741.14   233.5  740.42   243.2   739.1   252.9     738   262.6  738.24
   268.5   739.5   272.4  740.34   282.1  744.96   291.8  748.38   301.6  748.11
   311.3  747.33   329.7  745.38   338.4   744.6   347.2  745.29   355.9  747.56
   364.6  750.39     382  756.23
#Mann= 3 , 0 , 0
       0      .1       0   243.2    .045       0   268.5      .1       0
Bank Sta=243.2,268.5
XS Rating Curve= 0 ,0
Exp/Cntr=0.3,0.1

Type RM Length L Ch R = 1 ,16336.8 ,167.9,173.5,178.9
XS GIS Cut Line= 4
     1868614.744      527943.971     1868705.022       527989.11
     1868783.147      528030.777       1868857.8      528068.971
#Sta/Elev= 24
       0   748.9    18.4  744.06    27.5  742.25    36.7  741.14    45.9  740.68
    73.4  740.35    82.6  740.31   110.8  739.93   120.6  739.45   130.4     738
   140.3   736.1   142.5  735.95   150.1  735.43   157.5  736.52     160  736.89
   169.8  740.55   179.6  744.61   189.5  748.16   217.4  757.74   226.7  761.32
   236.1  765.26   245.4  769.34     264  777.79   273.3  782.27
#Mann= 3 , 0 , 0
       0      .1       0   142.5    .045       0   157.5      .1       0
Bank Sta=142.5,157.5
XS Rating Curve= 0 ,0
Exp/Cntr=0.3,0.1

Type RM Length L Ch R = 1 ,16163.3 ,352.4,372.2,391.8
XS GIS Cut Line= 2
     1868541.828      528034.249       1868732.8      528200.916
#Sta/Elev= 29
       0  764.03     9.8   759.8    19.5  755.45    29.2  751.05      39  746.59
    48.7  742.56    58.5  740.29    68.2  739.38      78  736.98    87.7  734.38
    91.1  733.96    97.5  733.17   106.1  733.42   107.2  733.45     117  734.61
   126.7  735.87   136.5     737   146.2  738.01     156  738.86   165.7  739.55
   175.5  740.15   185.2  740.72     195  741.57   204.7  743.51   214.5  746.47
   224.2  749.51     234  752.63   243.7  755.78   253.5   758.9
#Mann= 3 , 0 , 0
       0      .1       0    91.1    .045       0   107.2      .1       0
Bank Sta=91.1,107.2
XS Rating Curve= 0 ,0
Exp/Cntr=0.3,0.1

Type RM Length L Ch R = 1 ,15791.1 ,320.1,304.8,287.9
XS GIS Cut Line= 2
     1868354.328      528127.999     1868347.383      528416.193
#Sta/Elev= 22
       0   753.5    19.2  745.55    28.8  741.72    38.4  739.29      48   738.4
    57.7  738.05    86.5  737.72   134.5  736.97   144.1   736.8   153.8  736.47
   163.4  735.25   181.9  730.32   182.6  730.14   192.2   729.5   196.9  730.37
   201.8  731.28   211.4  735.43     221  740.04   230.6  743.91   249.8  751.36
   278.7   762.4   288.3  766.19
#Mann= 3 , 0 , 0
       0      .1       0   181.9    .045       0   196.9      .1       0
Bank Sta=181.9,196.9
XS Rating Curve= 0 ,0
Exp/Cntr=0.3,0.1

Type RM Length L Ch R = 1 ,15486.3 ,276.9,256.2,235.8
XS GIS Cut Line= 4
     1867927.244      528263.416     1868034.883      528315.499
     1868128.633      528407.513     1868284.883      528454.388
#Sta/Elev= 30
       0  761.32    27.6  749.35      46  741.74    55.2  738.39    64.4  736.23
    73.6  735.42   110.4  734.99   119.6  734.19     129  731.63   138.3  728.72
   147.7  726.79   157.1  725.78   175.9  724.39   201.2  723.05     204  722.96
   213.4  723.02   222.8  723.83   232.2  726.54   241.6  729.89   250.9  731.83
   279.7  733.46   298.9  735.38   308.5  736.82   327.7  740.88   346.9  745.56
   356.5  748.39   366.1  751.68   385.3  758.86   394.9  761.99   414.1  767.28
#Mann= 3 , 0 , 0
       0      .1       0   201.2    .045       0   222.8      .1       0
Bank Sta=201.2,222.8
XS Rating Curve= 0 ,0
Exp/Cntr=0.3,0.1

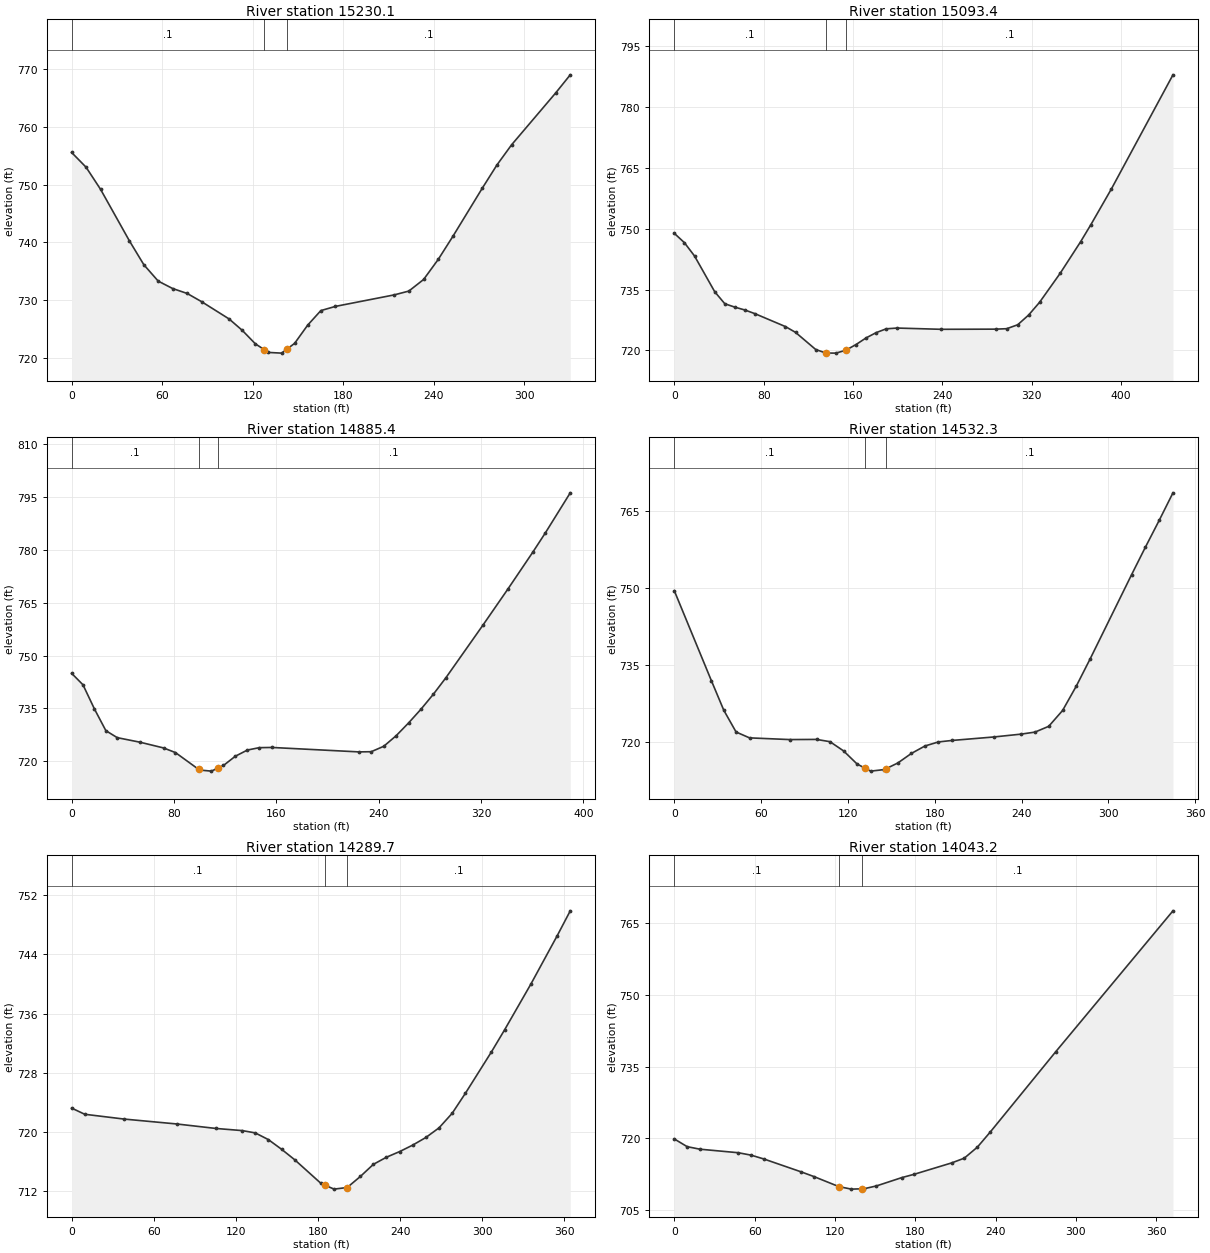
Type RM Length L Ch R = 1 ,15230.1 ,112.6,136.8,160.8
XS GIS Cut Line= 4
     1867972.383      528570.707     1868060.925      528607.166
     1868130.369      528607.166     1868288.356      528558.555
#Sta/Elev= 30
       0  755.57     9.6  753.01    19.2  749.18    38.3  740.26    47.9  736.11
    57.4  733.28      67  731.99    76.6  731.14    86.2  729.71   104.4  726.72
   113.1  724.75   121.8  722.41   127.6  721.42   130.5  720.92   139.2   720.8
   142.6  721.47   147.8  722.49   156.5  725.66   165.2  728.17   174.9   728.9
   213.8  730.89   223.5  731.55   233.3  733.56     243  737.04   252.7  741.03
   272.2  749.38   281.9   753.4   291.6  756.89   320.8  765.87   330.5  769.02
#Mann= 3 , 0 , 0
       0      .1       0   127.6    .045       0   142.6      .1       0
Bank Sta=127.6,142.6
XS Rating Curve= 0 ,0
Exp/Cntr=0.3,0.1

Type RM Length L Ch R = 1 ,15093.4 ,189.8,208,226.3
XS GIS Cut Line= 5
     1867960.231      528622.791     1868033.147      528690.499
     1868078.286      528768.624     1868121.689      528898.832
     1868211.967      528976.957
#Sta/Elev= 30
       0  748.87       9  746.58    18.1  743.29    36.2  734.47    45.2  731.52
    54.3  730.67    63.3  729.97    72.4  729.05    99.5  725.89   108.5  724.47
   126.6  720.24   135.6  719.38   144.6  719.35   153.5  720.06   162.7  721.47
   171.7   723.1   180.7   724.4   189.7  725.34   199.5  725.53   238.8  725.22
   287.8  725.26   297.6  725.37   307.4  726.34   317.2  728.74     327  731.88
   345.4  739.01   363.7  746.79   372.9     751   391.3  759.82   446.4  787.93
#Mann= 3 , 0 , 0
       0      .1       0   135.6    .045       0   153.5      .1       0
Bank Sta=135.6,153.5
XS Rating Curve= 0 ,0
Exp/Cntr=0.3,0.1

Type RM Length L Ch R = 1 ,14885.4 ,358.2,353.1,347
XS GIS Cut Line= 4
     1867892.522      528652.305     1867894.258      528714.805
     1867873.425      528796.402     1867767.522      529015.152
#Sta/Elev= 30
       0  744.99     8.9  741.72    17.9  734.83    26.8   728.7    35.7  726.72
    53.6  725.42    71.9   723.8    81.2  722.48    99.3  717.72     100  717.53
   109.3  717.22   114.3  718.07   118.7  718.82     128  721.45   137.4   723.2
   146.7  723.88   156.5  723.94   224.5  722.68   234.2  722.73     244  724.27
   253.7  727.27   263.4  730.89   273.1  734.79   282.8  739.05   292.6  743.73
   321.7  758.74   341.2  768.98   360.6  779.41   370.3  784.82   389.8  796.21
#Mann= 3 , 0 , 0
       0      .1       0    99.3    .045       0   114.3      .1       0
Bank Sta=99.3,114.3
XS Rating Curve= 0 ,0
Exp/Cntr=0.3,0.1

Type RM Length L Ch R = 1 ,14532.3 ,251.9,242.6,233
XS GIS Cut Line= 5
     1867611.272      528522.096     1867592.175      528560.291
     1867592.175      528615.846     1867593.911      528709.596
     1867571.342      528860.638
#Sta/Elev= 30
       0  749.46    25.6  732.01    34.2  726.25    42.7  722.02      52  720.88
    79.7  720.55    98.3  720.58   107.6  720.14     117  718.35   126.4  715.79
   131.5  715.05   135.8  714.42   145.1  714.72   146.5  714.91   154.5     716
   163.9  717.86   173.3  719.31   182.6  720.09     192  720.38   220.7  721.05
   239.8  721.61   249.3     722   258.8  723.12   268.4   726.2   277.9  730.95
   287.5  736.25   316.1  752.58   325.6   757.9   335.2  763.14   344.7  768.48
#Mann= 3 , 0 , 0
       0      .1       0   131.5    .045       0   146.5      .1       0
Bank Sta=131.5,146.5
XS Rating Curve= 0 ,0
Exp/Cntr=0.3,0.1

Type RM Length L Ch R = 1 ,14289.7 ,243.7,246.5,249
XS GIS Cut Line= 2
     1867276.203      528508.207     1867427.244      528839.805
#Sta/Elev= 28
       0  723.21     9.6  722.37    38.4  721.72    76.7  721.06   105.5  720.45
   124.7  720.16   134.2  719.85   143.8  718.94   153.4  717.64     163  716.22
   182.2  713.02   185.1  712.78   191.8  712.24   201.4  712.46     211  713.95
   220.5  715.59   230.1  716.56   239.7  717.32   249.3   718.2   258.9  719.23
   268.5  720.53   278.1   722.5   287.7  725.19   306.8  730.81   316.4  733.79
   335.6  739.98   354.8  746.51   364.4   749.9
#Mann= 3 , 0 , 0
       0      .1       0   185.1    .045       0   201.4      .1       0
Bank Sta=185.1,201.4
XS Rating Curve= 0 ,0
Exp/Cntr=0.3,0.1

Type RM Length L Ch R = 1 ,14043.2 ,218.1,223.8,229.4
XS GIS Cut Line= 4
     1867119.953      528666.193     1867123.425      528723.485
     1867173.772      528874.527     1867269.258      528997.791
#Sta/Elev= 21
       0  719.85     9.6  718.23    19.1   717.7    47.8  716.96    57.4  716.45
    66.8  715.66    94.9  712.94   104.2  711.98     123  709.86   132.3  709.34
   140.2  709.41   141.7  709.42     151  710.01   169.8  711.74   179.2  712.45
   207.2  714.83   216.6  715.82   226.4  718.13   236.1  721.32   284.8  738.06
   372.5   767.6
#Mann= 3 , 0 , 0
       0      .1       0     123    .045       0   140.2      .1       0
Bank Sta=123,140.2
XS Rating Curve= 0 ,0
Exp/Cntr=0.3,0.1

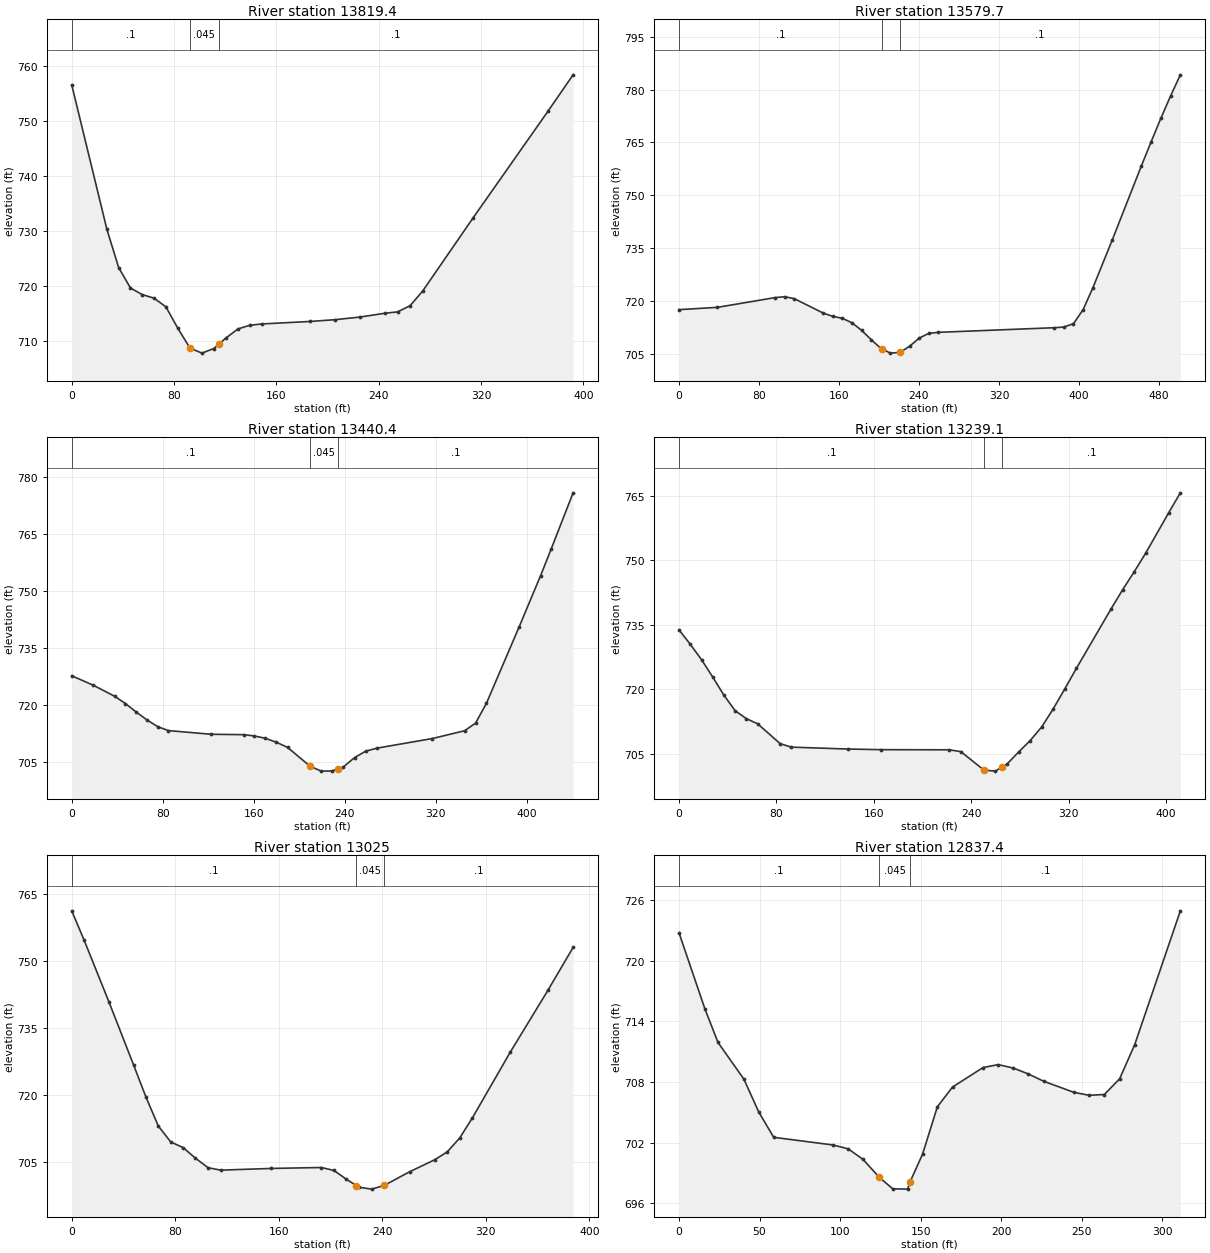
Type RM Length L Ch R = 1 ,13819.4 ,245.4,239.7,233.9
XS GIS Cut Line= 4
     1866930.717       528707.86     1866932.453      528772.096
     1866941.133      528893.624     1867029.675      529079.388
#Sta/Elev= 26
       0  756.59    27.5  730.34    36.7   723.4    45.9  719.71    55.1   718.5
    64.3  717.86    73.6  716.28      83  712.36    92.4  708.79   101.8  707.87
   111.1  708.71   114.8  709.46   120.5  710.61   129.9  712.26   139.2  712.93
   148.6  713.17   186.1  713.62   205.7  713.94   225.3  714.42   244.9  715.12
   254.7  715.36   264.5  716.49   274.3  719.14   313.5  732.36   372.3  751.82
   391.9  758.42
#Mann= 3 , 0 , 0
       0      .1       0    92.4    .045       0   114.8      .1       0
Bank Sta=92.4,114.8
XS Rating Curve= 0 ,0
Exp/Cntr=0.3,0.1

Type RM Length L Ch R = 1 ,13579.7 ,153,139.2,125.6
XS GIS Cut Line= 3
     1866640.786      528681.818     1866755.369      529008.207
     1866809.189      529154.041
#Sta/Elev= 30
       0  717.54    38.4  718.19    96.1  720.96   105.7  721.21   115.3  720.66
   144.1  716.59   153.7  715.64   163.4  715.07     173  713.82   182.6  711.68
   192.2  709.03   201.8  706.57     203   706.4   211.4   705.2     221   705.4
   230.6  707.15   240.2  709.46   249.8   710.8   259.4   711.1   375.1  712.41
   384.8   712.6   394.5  713.56   404.2  717.55   413.9  723.73   433.4  737.38
   462.5  758.39   472.2  765.19   481.9  771.84   491.6  778.16   501.4  784.18
#Mann= 3 , 0 , 0
       0      .1       0     203    .045       0     221      .1       0
Bank Sta=203,221
XS Rating Curve= 0 ,0
Exp/Cntr=0.3,0.1

Type RM Length L Ch R = 1 ,13440.4 ,202.6,201.3,199.9
XS GIS Cut Line= 4
     1866416.828      528867.582     1866567.869      528945.707
       1866670.3      529022.096       1866732.8      529150.568
#Sta/Elev= 30
       0  727.71    18.9  725.22    37.8   722.3    47.2  720.39    56.7  718.15
    66.1  716.09    75.6  714.31      85  713.27   122.8   712.3   151.2   712.2
   160.6  711.86     170  711.26   179.9   710.2   189.7  708.85   209.4  703.92
   219.2   702.6     229  702.65   233.8  703.17   238.8  703.72   248.7  706.18
   258.5  707.87   268.3  708.65   316.9  711.18   345.4  713.24     355  715.26
   364.5  720.45   393.1  740.46   412.1  754.05   421.6  761.21   440.7  775.88
#Mann= 3 , 0 , 0
       0      .1       0   209.4    .045       0   233.8      .1       0
Bank Sta=209.4,233.8
XS Rating Curve= 0 ,0
Exp/Cntr=0.3,0.1

Type RM Length L Ch R = 1 ,13239.1 ,227.7,214.1,200.4
XS GIS Cut Line= 4
     1866316.133      528996.055     1866371.689      529044.666
     1866481.064      529129.735     1866647.731       529239.11
#Sta/Elev= 30
       0  733.83     9.2   730.5    18.5  726.91    27.7  722.87    36.9  718.66
    46.1  715.05    55.4   713.2    64.6  712.02    83.1   707.4    92.3   706.6
   138.5  706.16   166.2  706.01   221.9  705.98   231.4  705.56   250.5  701.26
   259.8  701.03   265.5     702   269.3  702.65   278.8  705.44   288.3   708.1
   297.8  711.27   307.3  715.48   316.8  720.11   326.3  724.87   354.8  738.68
   364.3  743.13   373.8   747.3   383.3  751.66   402.2  761.04   411.7  765.63
#Mann= 3 , 0 , 0
       0      .1       0   250.5    .045       0   265.5      .1       0
Bank Sta=250.5,265.5
XS Rating Curve= 0 ,0
Exp/Cntr=0.3,0.1

Type RM Length L Ch R = 1 ,13025   ,179.2,187.6,196
XS GIS Cut Line= 3
     1866236.272      529384.943     1866328.286      529358.902
     1866619.953      529351.957
#Sta/Elev= 27
       0   761.3     9.6   754.7    28.7  740.91    47.8  726.73    57.4   719.5
    66.9  713.03    76.5  709.46    86.1  708.19    95.6  705.82   105.4  703.68
   115.1  703.14     154  703.52   192.9  703.73   202.6  703.07   212.3  701.08
   219.9  699.69     222   699.3   231.8  698.88   241.5  699.72     261  702.76
   280.4  705.46   290.1  707.22   299.8  710.35   309.6  714.87   338.8  729.58
   367.9  743.45   387.4  753.09
#Mann= 3 , 0 , 0
       0      .1       0   219.9    .045       0   241.5      .1       0
Bank Sta=219.9,241.5
XS Rating Curve= 0 ,0
Exp/Cntr=0.3,0.1

Type RM Length L Ch R = 1 ,12837.4 ,104,104.8,105.4
XS GIS Cut Line= 4
     1866292.777      529496.529     1866331.839      529506.295
     1866444.687      529547.527     1866585.746      529600.696
#Sta/Elev= 27
       0  722.78    16.1  715.24    24.2  711.92    40.3  708.28    49.5  705.03
    58.8  702.52    95.7  701.76     105  701.38   114.2  700.34   124.4  698.55
   132.7  697.42   141.9  697.39  143.53  698.14   151.2  700.86   160.4  705.55
   169.8   707.5   188.7  709.43   198.1  709.72   207.5  709.38   216.9  708.79
   226.4  708.07   245.2  706.97   254.6  706.68     264  706.76   273.5  708.31
   282.9  711.71   311.2  724.95
#Mann= 3 , 0 , 0
       0      .1       0   124.4    .045       0  143.53      .1       0
Bank Sta=124.4,143.53
XS Rating Curve= 0 ,0
Exp/Cntr=0.3,0.1

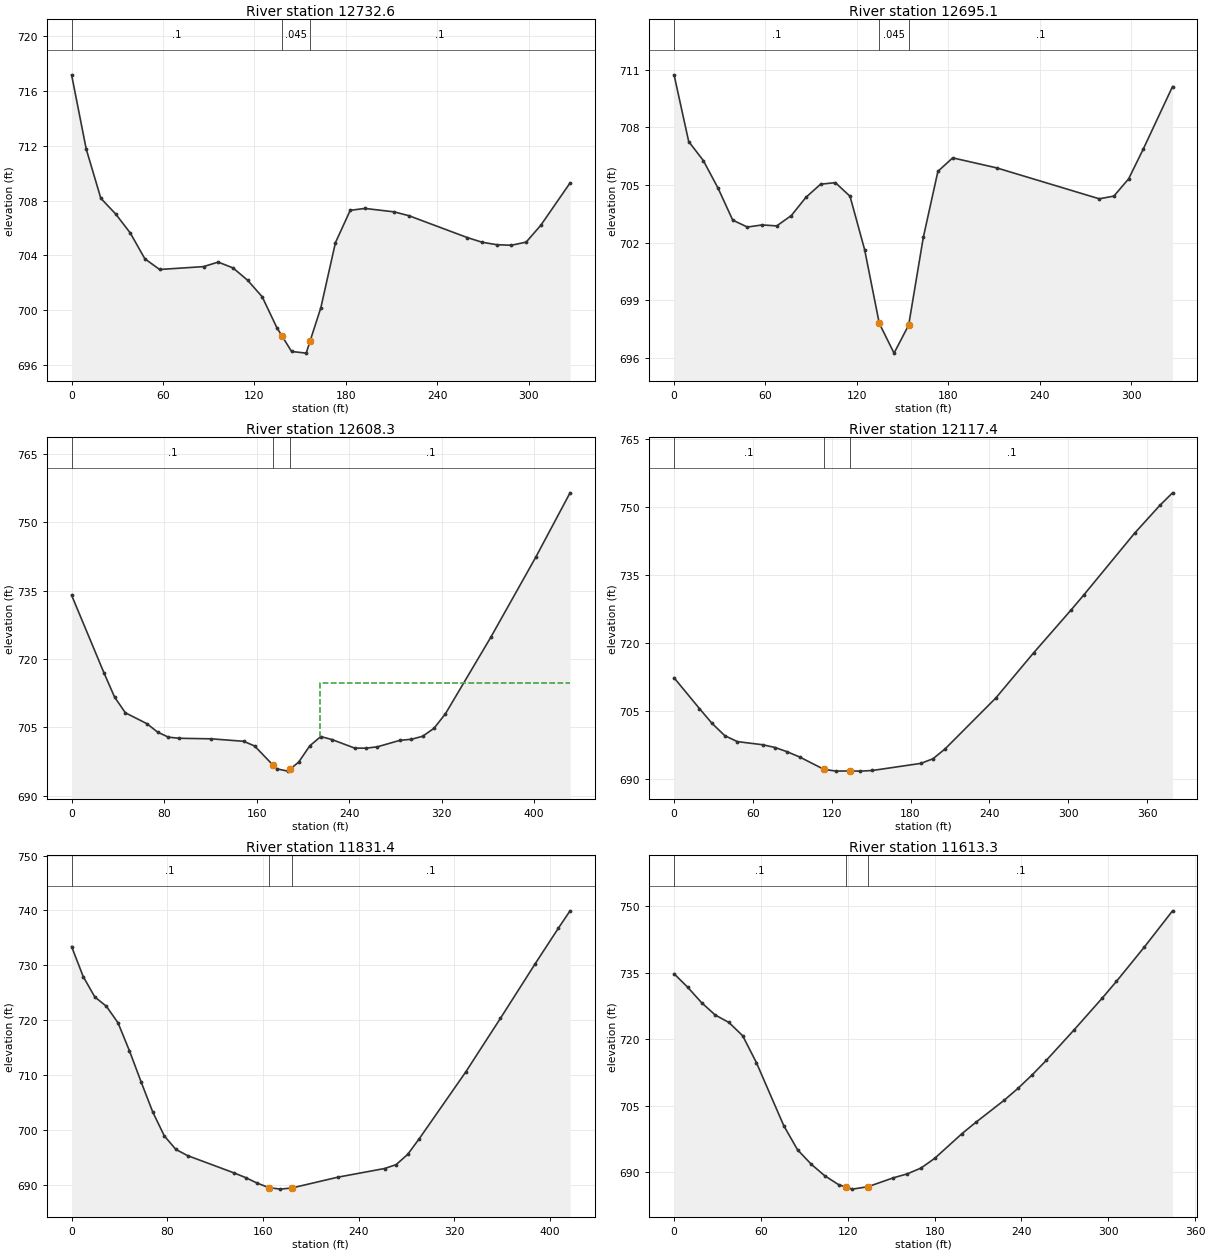
Type RM Length L Ch R = 1 ,12732.6 ,37.5,37.5,37.5
XS GIS Cut Line= 2
     1866250.459      529583.335     1866554.279      529704.862
#Sta/Elev= 30
       0  717.19     9.6  711.77    19.2  708.17    28.9  707.03    38.5  705.64
    48.1  703.75    57.8  702.97    86.6  703.18    96.2  703.51   105.9  703.09
   115.5  702.19   125.1  700.98   134.7  698.73   138.2   698.1   144.4  696.98
     154  696.86  156.55  697.74   163.6  700.17   173.2  704.93   182.9  707.29
   192.5  707.43   211.7  707.18   221.4   706.9   259.8   705.3   269.5  704.96
   279.1  704.78   288.7  704.74   298.4  704.97     308   706.2   327.2  709.29
#Mann= 3 , 0 , 0
       0      .1       0   138.2    .045       0  156.55      .1       0
Bank Sta=138.2,156.55
XS Rating Curve= 0 ,0
Exp/Cntr=0.3,0.1

Type RM Length L Ch R = 1 ,12695.1 ,75.1,86.7,98.5
XS GIS Cut Line= 2
     1866241.779      529620.227     1866545.598      529741.755
#Sta/Elev= 26
       0  710.74     9.6  707.27    19.2  706.28    28.9  704.84    38.5  703.18
    48.1  702.82    57.8  702.93    67.4  702.88      77  703.42    86.6  704.37
    96.2  705.05   105.9  705.13   115.5  704.42   125.1  701.64   134.7  697.81
   144.4  696.26     154  697.72   163.6  702.28   173.2  705.72   182.9  706.42
   211.7   705.9   279.1  704.29   288.7  704.43   298.4  705.33     308  706.88
   327.2  710.13
#Mann= 3 , 0 , 0
       0      .1       0   134.7    .045       0     154      .1       0
Bank Sta=134.7,154
XS Rating Curve= 0 ,0
Exp/Cntr=0.3,0.1

Type RM Length L Ch R = 1 ,12608.3 ,487.7,490.9,493.6
XS GIS Cut Line= 4
     1866206.758      529607.166     1866305.717      529718.277
     1866347.383       529770.36     1866486.272      529935.291
#Sta/Elev= 30
       0  734.01    27.9  717.03    37.2  711.64    46.5   708.2    65.1  705.81
    74.4  703.96    83.7  702.85      93   702.6   120.9  702.48   148.8  701.94
   158.3  700.91   174.3  696.68   177.4   695.9   186.9  695.39   189.3  695.89
   196.4  697.37     206  700.94   215.5  702.98   225.3  702.31   244.9  700.44
   254.7  700.43   264.5  700.73   284.1  702.16   293.9  702.38   303.7  703.05
   313.5  704.81   323.3  707.97   362.5  724.75   401.7  742.47   431.1  756.48
#Mann= 3 , 0 , 0
       0      .1       0   174.3    .045       0   189.3      .1       0
#XS Ineff= 2 , 0
                          215.23          714.82
Permanent Ineff=
       F       F
Bank Sta=174.3,189.3
XS Rating Curve= 0 ,0
Exp/Cntr=0.3,0.1

Type RM Length L Ch R = 1 ,12117.4 ,309.5,286,262.6
XS GIS Cut Line= 4
     1865807.453      529779.041     1865852.592      529841.541
     1865918.564      529952.652     1866038.356      530077.652
#Sta/Elev= 24
       0  712.36    19.3  705.59    28.9  702.32    38.6  699.61    48.2   698.3
    67.5  697.61    77.1  696.99    86.3  696.04    95.6  694.91     114   692.2
   123.2  691.81   133.9  691.84   141.7   691.8   150.9  691.94   187.9  693.51
   197.1  694.53   206.3   696.7   244.8  707.88   273.6  717.83   302.5   727.4
   312.1  730.69   350.6  744.23   369.8  750.35   379.4   753.1
#Mann= 3 , 0 , 0
       0      .1       0     114    .045       0   133.9      .1       0
Bank Sta=114,133.9
XS Rating Curve= 0 ,0
Exp/Cntr=0.3,0.1

Type RM Length L Ch R = 1 ,11831.4 ,227.2,218.1,208.8
XS GIS Cut Line= 2
     1865578.286      530110.638     1865994.953      530110.638
#Sta/Elev= 27
       0  733.44     9.7  727.98    19.4  724.26    29.1  722.56    38.8  719.56
    48.4  714.44    58.1  708.81    67.8  703.34    77.5  698.96    87.2   696.5
    96.9  695.38   135.7  692.23   145.4  691.38   155.2  690.36   164.7  689.56
   174.4  689.27   184.1  689.48   222.9  691.46   261.6  693.02   271.3  693.73
     281   695.6   290.7  698.47   329.5   710.6   358.5  720.37   387.6  730.32
     407   736.8   416.7  739.94
#Mann= 3 , 0 , 0
       0      .1       0   164.7    .045       0   184.1      .1       0
Bank Sta=164.7,184.1
XS Rating Curve= 0 ,0
Exp/Cntr=0.3,0.1

Type RM Length L Ch R = 1 ,11613.3 ,320.6,343.2,365.4
XS GIS Cut Line= 3
     1865677.244       530364.11     1865859.536      530284.249
     1866003.633      530265.152
#Sta/Elev= 30
       0  734.82     9.5  731.75      19   728.3    28.4  725.52    37.9  723.83
    47.4  720.84    56.9  714.76    75.8  700.55    85.3  695.12    94.8  691.85
   104.2  689.23   113.7  687.25     119  686.69   123.2  686.24     134  686.79
   151.6   688.8   161.1  689.68   170.6  690.99   180.1  693.19     199  698.78
   208.7  701.36   228.1  706.29   237.8  709.02   247.5  712.04   257.2  715.29
   276.5   722.2   295.9  729.35   305.6  733.08     325  740.87   344.4  749.01
#Mann= 3 , 0 , 0
       0      .1       0     119    .045       0     134      .1       0
Bank Sta=119,134
XS Rating Curve= 0 ,0
Exp/Cntr=0.3,0.1