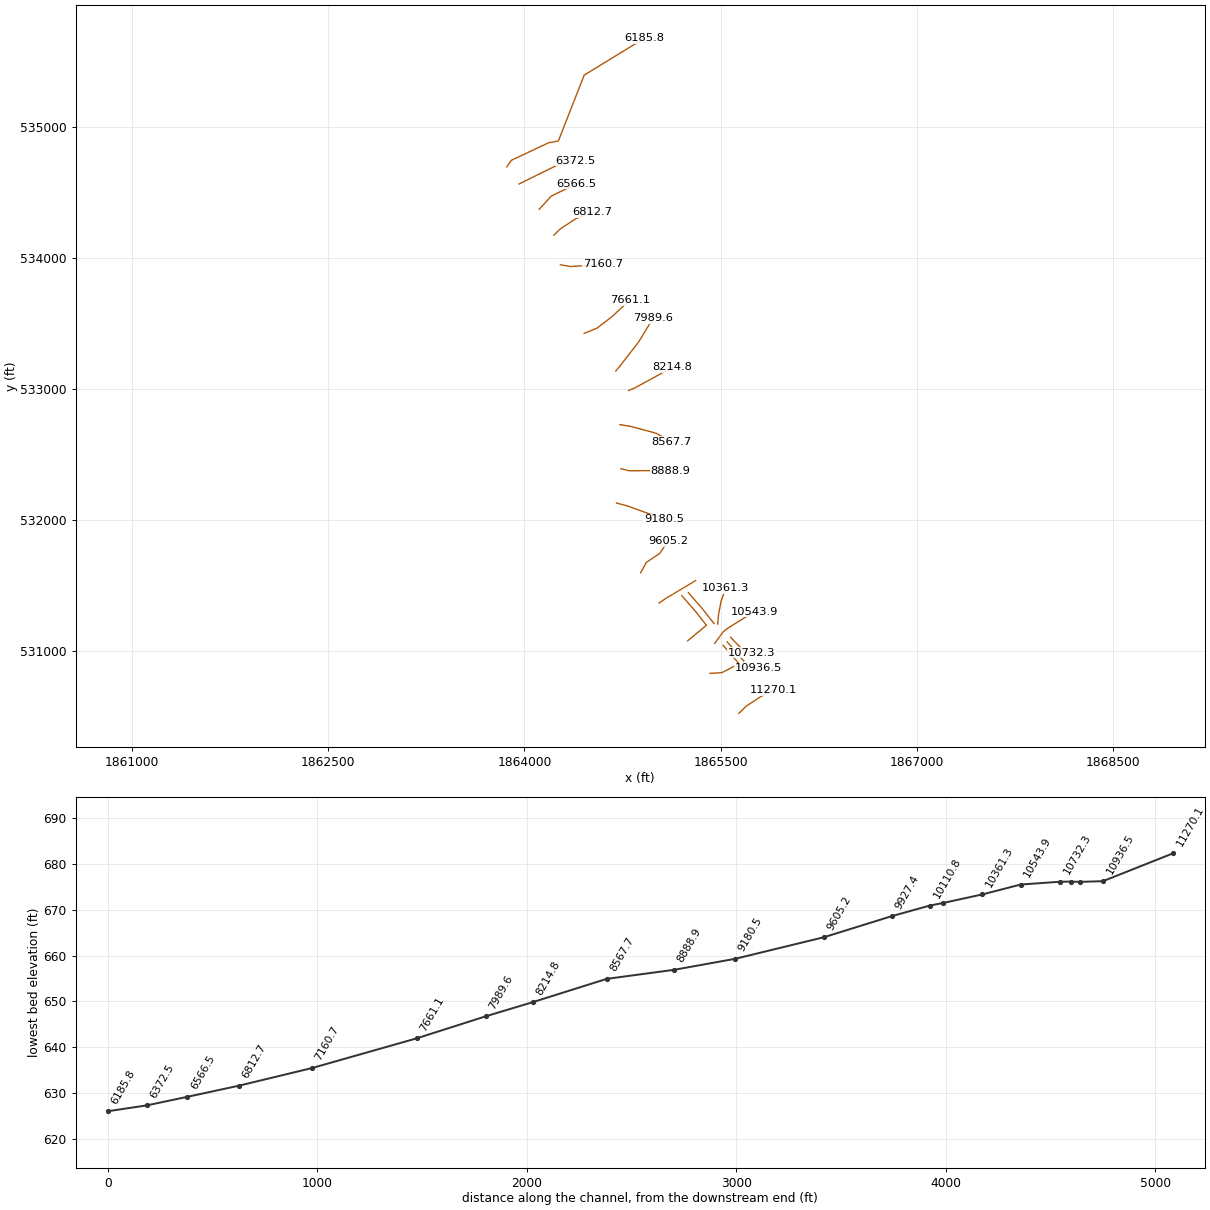
HEC-RAS study LEATHRWDFK.prj: LEATHRWDFK

--- LEATHRWDFK.g01 (geometry) --- (continued)

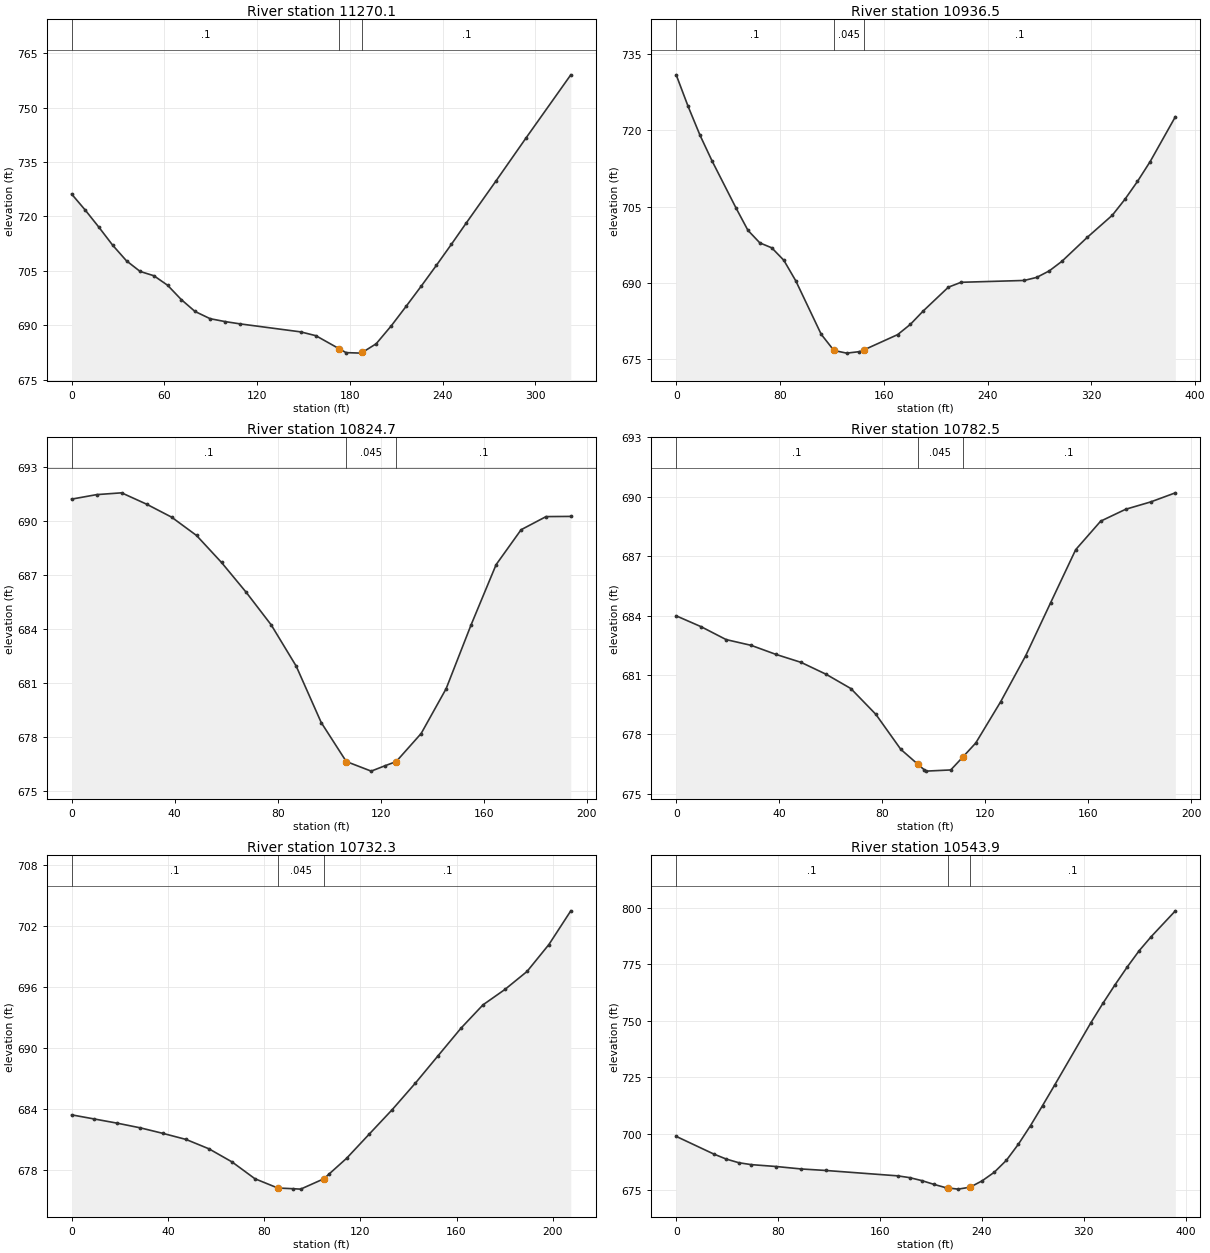
Type RM Length L Ch R = 1 ,11270.1 ,335.9,333.6,333.8
XS GIS Cut Line= 4
     1865637.314       530520.36     1865694.606      530575.916
     1865809.189      530650.568     1865904.675      530697.443
#Sta/Elev= 29
       0  726.19     8.9  721.72    17.7  717.01    26.6  712.05    35.5  707.76
    44.3  704.84    53.2  703.65    62.1  701.02    70.9  697.09    79.8   693.8
    89.6   691.8    99.3     691   109.1  690.36   148.2  688.16     158  687.11
   173.1   683.5   177.5  682.44   187.3   682.3   188.1  682.51     197  684.88
   206.8  689.85   216.6  695.34   226.2  700.81   235.9  706.49   245.6  712.29
   255.2  718.16   274.6  729.86   293.9  741.64   322.9  759.08
#Mann= 3 , 0 , 0
       0      .1       0   173.1    .045       0   188.1      .1       0
Bank Sta=173.1,188.1
XS Rating Curve= 0 ,0
Exp/Cntr=0.3,0.1

Type RM Length L Ch R = 1 ,10936.5 ,142.3,111.8,78.1
XS GIS Cut Line= 4
     1865416.828      530825.916     1865508.842      530831.124
     1865604.328      530881.471     1865788.356      530865.846
#Sta/Elev= 30
       0  730.85     9.2  724.65    18.4  718.97    27.6  713.98    46.1  704.73
    55.3  700.34    64.5  697.87    73.7   696.9      83  694.45    92.2  690.42
   111.8  679.93   121.6  676.76   131.4  676.24   141.2  676.53   144.6  676.86
   170.7  679.87   180.5  681.88   190.3  684.48   209.8  689.18   219.6  690.14
   268.2   690.5   277.9   691.1   287.6  692.38   297.3  694.25   316.8  698.94
   336.2   703.3   345.9  706.42   355.6  709.94   365.4  713.84   384.8  722.63
#Mann= 3 , 0 , 0
       0      .1       0   121.6    .045       0   144.6      .1       0
Bank Sta=121.6,144.6
XS Rating Curve= 0 ,0
Exp/Cntr=0.3,0.1

Type RM Length L Ch R = 1 ,10824.7 ,42.2,42.2,42.2
XS GIS Cut Line= 2
     1865518.037      531039.498      1865644.99      530893.013
#Sta/Elev= 23
       0   691.2     9.7  691.45    19.4  691.55    29.1  690.92    38.8   690.2
    48.5  689.18    58.2  687.68    67.8  686.02    77.5  684.21    87.2  681.92
    96.9  678.79   106.6  676.63   106.7  676.62   116.3  676.09   121.7  676.39
     126  676.62   135.7  678.18   145.4  680.67   155.1  684.22   164.8  687.56
   174.5   689.5   184.2  690.23   193.8  690.24
#Mann= 3 , 0 , 0
       0      .1       0   106.7    .045       0     126      .1       0
Bank Sta=106.7,126
XS Rating Curve= 0 ,0
Exp/Cntr=0.3,0.1

Type RM Length L Ch R = 1 ,10782.5 ,51.6,50.2,51.2
XS GIS Cut Line= 2
     1865548.419      531066.625     1865675.372       530920.14
#Sta/Elev= 24
       0  683.99     9.7  683.44    19.4  682.79    29.1   682.5    38.8  682.04
    48.5  681.64    58.2  681.04    67.8  680.32    77.5  679.02    87.2  677.25
   93.89  676.49    96.2  676.23    96.9  676.15   106.6  676.21   111.2  676.85
   116.3  677.57     126  679.66   135.7  681.98   145.4  684.66   155.1  687.33
   164.8  688.77   174.5  689.37   184.2  689.74   193.8   690.2
#Mann= 3 , 0 , 0
       0      .1       0   93.89    .045       0   111.2      .1       0
Bank Sta=93.89,111.2
XS Rating Curve= 0 ,0
Exp/Cntr=0.3,0.1

Type RM Length L Ch R = 1 ,10732.3 ,154.9,188.3,219.9
XS GIS Cut Line= 3
     1865574.461      531101.347     1865687.308      530985.244
     1865732.881      530984.159
#Sta/Elev= 25
       0  683.42     9.5  683.01      19   682.6    28.6  682.14    38.1  681.59
    47.6     681    57.1  680.08    66.7  678.79    76.2  677.14    85.7  676.23
    92.1  676.16    95.2  676.12   104.8  677.13   107.1  677.62   114.3  679.15
   123.8  681.55   133.3  683.94   142.9  686.54   152.4  689.25   161.9  691.95
     171  694.23   180.1  695.74   189.3  697.51   198.4  700.16   207.5  703.47
#Mann= 3 , 0 , 0
       0      .1       0    85.7    .045       0   104.8      .1       0
Bank Sta=85.7,104.8
XS Rating Curve= 0 ,0
Exp/Cntr=0.3,0.1

Type RM Length L Ch R = 1 ,10543.9 ,162.3,182.6,201.7
XS GIS Cut Line= 4
     1865453.286      531055.082     1865517.522      531141.888
     1865553.981      531171.402     1865755.369      531296.402
#Sta/Elev= 30
       0  698.83    29.4  691.05    39.3   688.8    49.1  687.19    58.9  686.34
    78.5  685.51    98.2  684.42   117.4  683.76   173.9  681.38   183.3  680.59
   192.8  679.28   202.3  677.62   211.8  676.13   213.2  676.04   221.3  675.51
   230.7  676.36   240.2  679.18   249.7  682.96   259.2  688.23   268.7  695.41
   278.2  703.61   287.6  712.41   297.1  721.48   325.6   749.1     335  757.63
   344.5  765.82     354  773.62   363.5  780.91     373  787.17   391.9  798.53
#Mann= 3 , 0 , 0
       0      .1       0   213.2    .045       0   230.7      .1       0
Bank Sta=213.2,230.7
XS Rating Curve= 0 ,0
Exp/Cntr=0.3,0.1

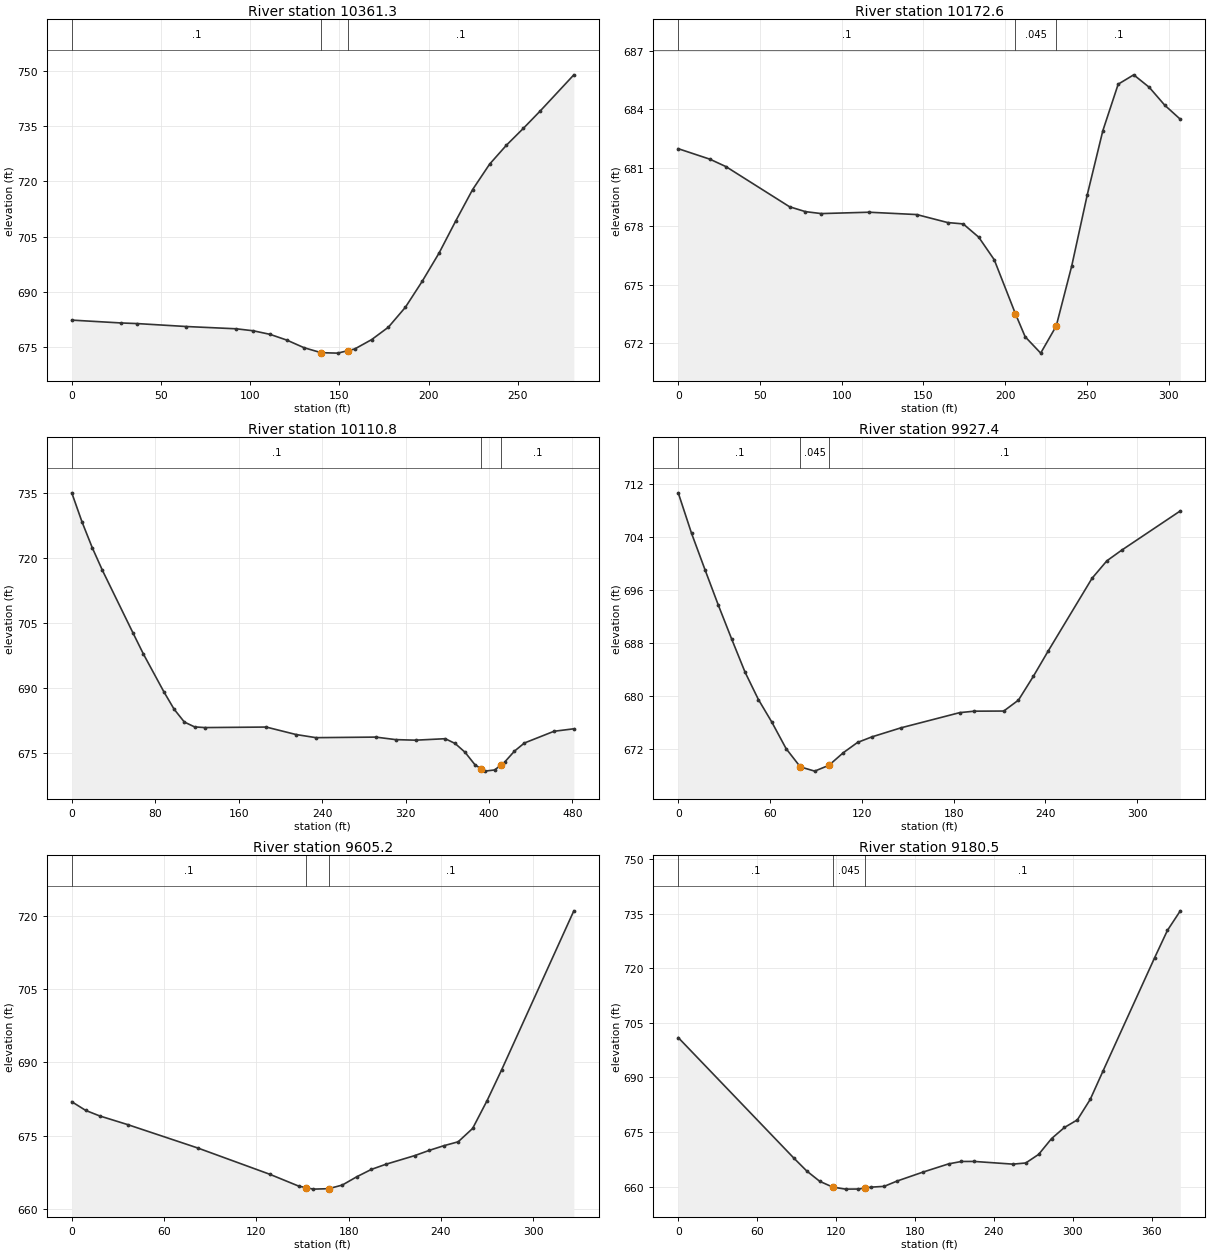
Type RM Length L Ch R = 1 ,10361.3 ,168.4,188.8,210
XS GIS Cut Line= 4
     1865475.856      531202.652       1865482.8      531275.568
     1865501.897      531377.999     1865538.356      531475.221
#Sta/Elev= 25
       0  682.33    27.5  681.56    36.6  681.39    64.1  680.59    92.2  679.97
   101.7  679.43   111.1  678.46   120.6  676.88   130.1  674.84   139.7  673.48
     149  673.36   154.7  674.03   158.5  674.48     168  677.03   177.4  680.41
   186.9  685.81   196.3  692.84   205.8  700.56   215.2  709.34   224.6  717.81
   234.1   724.7   243.5  729.84     253  734.42   262.4  739.12   281.3  748.97
#Mann= 3 , 0 , 0
       0      .1       0   139.7    .045       0   154.7      .1       0
Bank Sta=139.7,154.7
XS Rating Curve= 0 ,0
Exp/Cntr=0.3,0.1

Type RM Length L Ch R = 1 ,10172.6 ,61.6,61.8,61.6
XS GIS Cut Line= 3
     1865448.078      531206.124       1865357.8      531320.707
     1865251.897      531442.235
#Sta/Elev= 24
       0  681.97    19.4  681.43    29.2  681.05    68.1  678.99    77.8  678.74
    87.5  678.64   116.7  678.71   145.9  678.59   164.8  678.18   174.3  678.11
   183.8  677.43   193.3  676.27   206.2  673.51   212.2  672.32   221.7  671.48
   231.2  672.87   240.7  675.96   250.2  679.61   259.7  682.89   269.1  685.28
   278.6  685.76   288.1  685.12   297.6   684.2   307.1  683.48
#Mann= 3 , 0 , 0
       0      .1       0   206.2    .045       0   231.2      .1       0
Bank Sta=206.2,231.2
XS Rating Curve= 0 ,0
Exp/Cntr=0.3,0.1

Type RM Length L Ch R = 1 ,10110.8 ,224.5,183.4,142.2
XS GIS Cut Line= 4
     1865246.689       531074.18     1865390.186       531193.13
     1865307.453      531298.138      1865201.55      531419.666
#Sta/Elev= 30
       0  734.96     9.8  728.28    19.6  722.36    29.4  717.12    58.9  702.62
    68.7  697.86    88.3  689.18    98.1  685.18   107.9  682.23   117.7  681.11
   127.5  680.95   186.4  681.07     215  679.35   234.1  678.63   291.4  678.76
   310.5  678.18   329.6  678.05     358  678.39   367.5  677.29     377  675.27
   386.4  672.43  392.09   671.5   395.9  670.93   405.4   671.2   411.5  672.35
   414.9  672.99   424.4  675.54   433.9   677.4   462.3   680.1   481.3  680.67
#Mann= 3 , 0 , 0
       0      .1       0  392.09    .045       0   411.5      .1       0
Bank Sta=392.09,411.5
XS Rating Curve= 0 ,0
Exp/Cntr=0.3,0.1

Type RM Length L Ch R = 1 ,9927.4  ,321,322.2,323.5
XS GIS Cut Line= 4
     1865027.939      531362.374     1865078.286      531397.096
     1865142.522      531435.291     1865307.453      531534.249
#Sta/Elev= 26
       0  710.61     8.7   704.5    17.5     699    26.2  693.66      35   688.5
    43.7  683.53    52.4  679.41    61.2  675.99    70.5     672    79.8  669.24
    89.2   668.6    98.5  669.48   107.9  671.38   117.2  672.93   126.6  673.77
   145.5  675.13     184  677.43   193.6  677.65   212.8  677.67   222.4  679.32
   232.1   682.9   241.7  686.68   270.5  697.71   280.2  700.35   289.8  701.94
   328.2  707.88
#Mann= 3 , 0 , 0
       0      .1       0    79.8    .045       0    98.5      .1       0
Bank Sta=79.8,98.5
XS Rating Curve= 0 ,0
Exp/Cntr=0.3,0.1

Type RM Length L Ch R = 1 ,9605.2  ,445.9,424.7,403.2
XS GIS Cut Line= 4
     1864887.314      531593.277     1864930.717      531673.138
     1865033.147      531740.846     1865095.647      531834.596
#Sta/Elev= 22
       0  681.95     9.1  680.16    18.2  679.03    36.4  677.25    81.8  672.47
   128.7  667.07   147.6  664.63     152  664.34     157  664.02     167  664.11
   175.9  664.86   185.3  666.56   194.8  668.07   204.2  669.12   223.1  670.91
   232.5  671.98   241.8  672.92   251.2  673.73   260.6  676.47     270  682.18
   279.4  688.45   326.4  721.11
#Mann= 3 , 0 , 0
       0      .1       0     152    .045       0     167      .1       0
Bank Sta=152,167
XS Rating Curve= 0 ,0
Exp/Cntr=0.3,0.1

Type RM Length L Ch R = 1 ,9180.5  ,283.5,291.6,299.6
XS GIS Cut Line= 3
     1864703.286      532126.263     1864788.356      532103.693
     1865064.397      532002.999
#Sta/Elev= 26
       0  700.96      88   667.8    97.8  664.26   107.6  661.45   117.4  659.87
   127.2   659.3     137  659.33   141.8  659.58   146.8  659.85   156.6  660.06
   166.4  661.52     186  663.97   205.6  666.24   215.3   666.9   225.1  666.91
   254.5  666.17   264.3  666.49   274.1  668.86   283.9   673.2   293.7  676.25
   303.5  678.34   313.3  683.97   323.1  691.83   362.3  722.93     372  730.42
   381.8   735.8
#Mann= 3 , 0 , 0
       0      .1       0   117.4    .045       0   141.8      .1       0
Bank Sta=117.4,141.8
XS Rating Curve= 0 ,0
Exp/Cntr=0.3,0.1

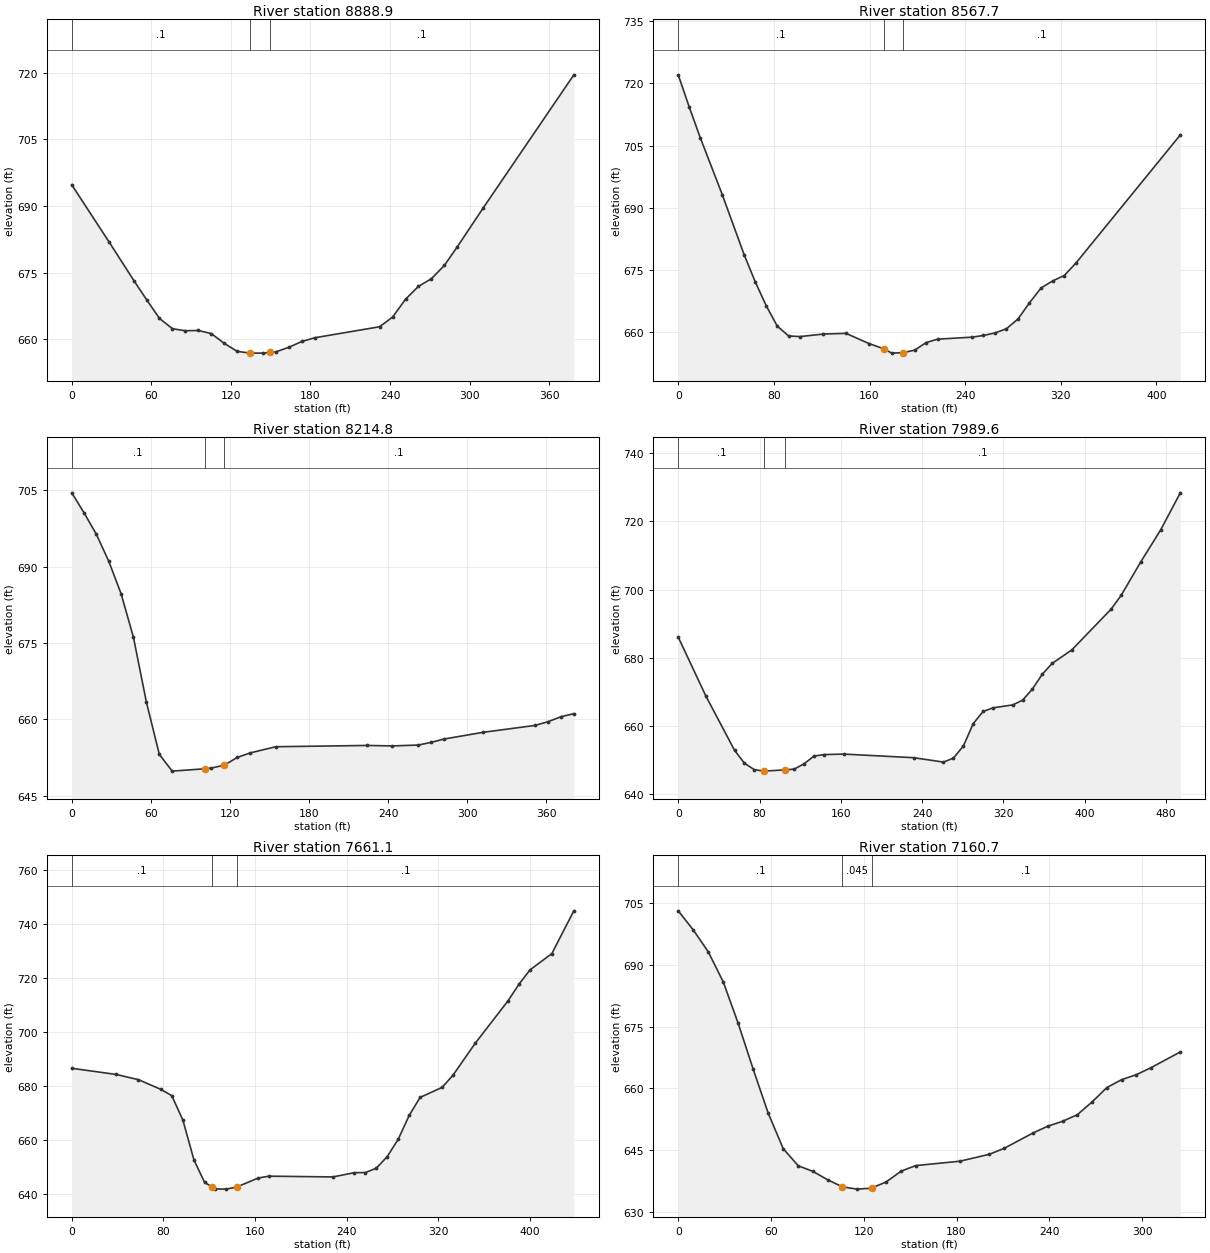
Type RM Length L Ch R = 1 ,8888.9  ,326.8,321.2,314.8
XS GIS Cut Line= 3
     1864736.272      532388.416     1864800.508      532372.791
     1865113.008      532374.527
#Sta/Elev= 27
       0  694.74    28.3  681.82    47.2  673.04    56.7   668.8    66.1  664.72
    75.9  662.39    85.6  661.93    95.4  661.99   105.2   661.3   114.9  659.11
   124.7   657.3   134.3  656.91   144.2   656.9   149.3  657.05     154  657.19
   163.8  658.23   173.5  659.52   183.3  660.36   232.1  662.83   241.9     665
   251.7  669.02   261.4  671.91   271.2  673.63     281  676.64   290.7   680.8
   310.2  689.52   378.6  719.48
#Mann= 3 , 0 , 0
       0      .1       0   134.3    .045       0   149.3      .1       0
Bank Sta=134.3,149.3
XS Rating Curve= 0 ,0
Exp/Cntr=0.3,0.1

Type RM Length L Ch R = 1 ,8567.7  ,335.9,352.9,370.2
XS GIS Cut Line= 4
     1864729.328      532725.221     1864810.925      532711.332
     1865005.369      532659.249     1865125.161      532595.013
#Sta/Elev= 30
       0  722.06     9.2  714.29    18.4  706.92    36.8  693.18    55.2  678.62
    64.4  672.14    73.6  666.37    82.8  661.45    92.4  659.07   101.9  658.92
   121.1  659.52   140.3   659.7   159.5  657.25   171.9  655.98   178.6  654.93
   188.2  655.05   197.8  655.65   207.4  657.48     217   658.3   245.7  658.78
   255.3  659.19   264.9  659.79   274.5   660.8   284.1  663.13   293.8  667.05
   303.5  670.64   313.2  672.35   322.9  673.65   332.6  676.63     420  707.57
#Mann= 3 , 0 , 0
       0      .1       0   171.9    .045       0   188.2      .1       0
Bank Sta=171.9,188.2
XS Rating Curve= 0 ,0
Exp/Cntr=0.3,0.1

Type RM Length L Ch R = 1 ,8214.8  ,215.7,225.2,234.4
XS GIS Cut Line= 3
       1864795.3      532985.638     1864838.703      533002.999
     1865132.106      533162.721
#Sta/Elev= 25
       0  704.48     9.4  700.52    18.7  696.31      28  691.09    37.4  684.68
    46.8   676.1    56.6   663.4    66.4  653.14    76.2  649.85   100.8  650.31
   105.7  650.45   115.8  651.02   125.4  652.53   135.2  653.42   154.8  654.64
   223.6  654.89   243.2   654.8   262.9  654.97   272.7  655.51   282.6  656.16
     312  657.47   351.3  658.82   361.2  659.55     371  660.52   380.8  661.13
#Mann= 3 , 0 , 0
       0      .1       0   100.8    .045       0   115.8      .1       0
Bank Sta=100.8,115.8
XS Rating Curve= 0 ,0
Exp/Cntr=0.3,0.1

Type RM Length L Ch R = 1 ,7989.6  ,334.2,328.5,323.5
XS GIS Cut Line= 4
     1864698.078      533134.943     1864727.592      533169.666
     1864871.689       533355.43       1864982.8      533537.721
#Sta/Elev= 30
       0  686.07    27.3  668.73    55.4  652.88    65.2  649.05      75  647.16
    84.8  646.75   105.5  647.14   114.1  647.33   123.9  648.92   133.7  651.17
   143.5   651.6   163.1  651.75   231.7  650.69   261.1   649.4   270.9  650.57
   280.7  654.14   290.4  660.71   300.1  664.25   309.8  665.32   329.2  666.18
   338.9  667.55   348.6  670.83   358.3  675.18     368  678.34   387.4  682.32
   426.2  694.32   435.9  698.29   455.3  708.17   474.8   717.5   494.2  728.41
#Mann= 3 , 0 , 0
       0      .1       0    84.8    .045       0   105.5      .1       0
Bank Sta=84.8,105.5
XS Rating Curve= 0 ,0
Exp/Cntr=0.3,0.1

Type RM Length L Ch R = 1 ,7661.1  ,514.4,500.4,485.3
XS GIS Cut Line= 4
     1864455.022      533421.402     1864553.981      533461.332
     1864665.092      533546.402     1864805.717       533676.61
#Sta/Elev= 30
       0  686.65    38.8  684.36    58.2  682.44    77.6  678.88    87.3  676.53
      97  667.46   106.7  652.72     116  644.43   122.1  642.87   125.4  642.03
   134.7  641.96     144  642.73   162.7  646.06     172  646.75     228  646.47
   246.6  648.04   256.2  648.08   265.8  649.68   275.4     654     285  660.43
   294.6  669.25   304.1  675.88   323.3  679.57   332.9  684.14   352.1  695.85
   380.8  711.56   390.4  717.73     400  723.02   419.1  729.06   438.3  744.87
#Mann= 3 , 0 , 0
       0      .1       0   122.1    .045       0     144      .1       0
Bank Sta=122.1,144
XS Rating Curve= 0 ,0
Exp/Cntr=0.3,0.1

Type RM Length L Ch R = 1 ,7160.7  ,335.1,348,360.9
XS GIS Cut Line= 3
     1864274.467      533945.707     1864350.856      533931.818
     1864597.383      533947.443
#Sta/Elev= 30
       0  703.14     9.7   698.5    19.4  693.18    29.1  685.87    38.8  675.75
    48.5   664.6    58.2  653.92    67.9  645.31    77.6  641.15    87.1  639.78
    96.6  637.75   106.1  636.03   115.6  635.47     125   635.7   134.6  637.25
   144.2  639.85   153.6  641.19   182.2  642.26   201.2  643.94   210.6  645.36
   229.7  649.17   239.2   650.8   248.7  651.98   258.2  653.59   267.7  656.69
   277.2  660.17   286.7  662.08   296.2  663.29   305.7  664.99   324.7  668.83
#Mann= 3 , 0 , 0
       0      .1       0   106.1    .045       0     125      .1       0
Bank Sta=106.1,125
XS Rating Curve= 0 ,0
Exp/Cntr=0.3,0.1

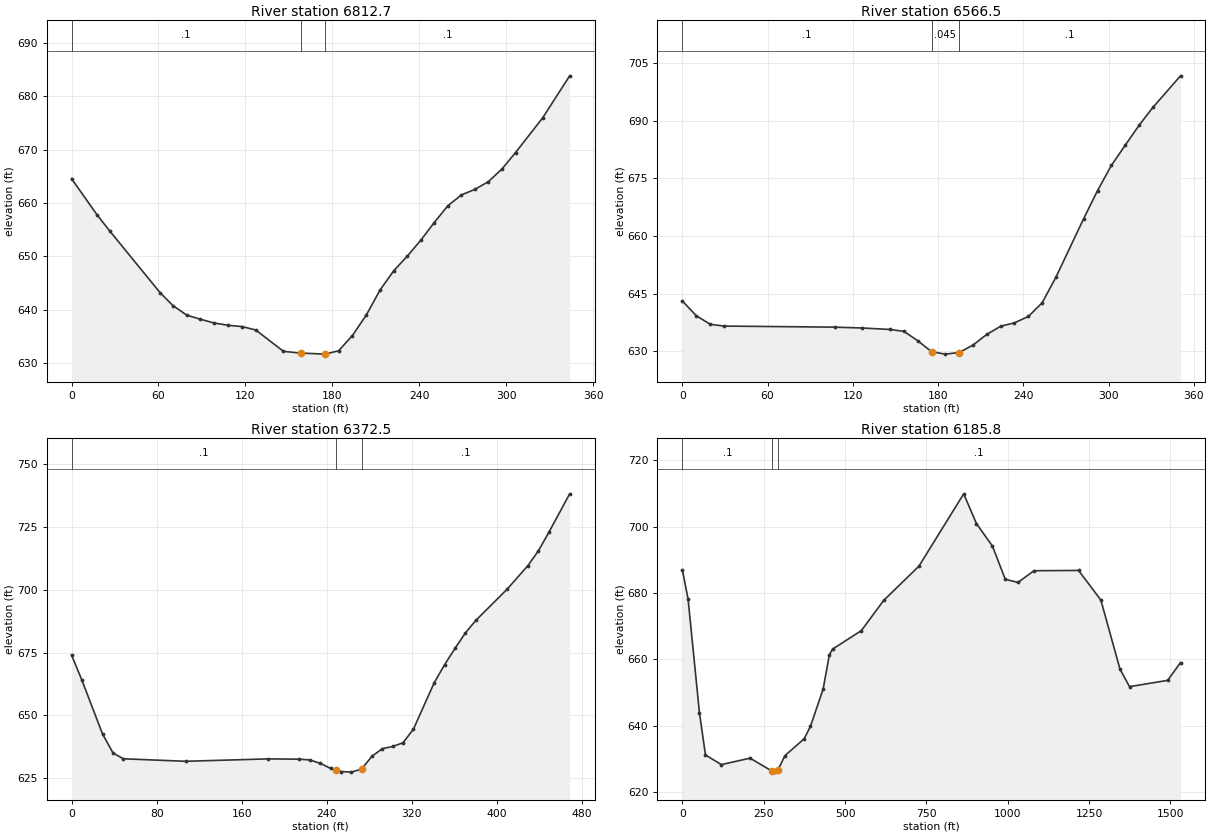
Type RM Length L Ch R = 1 ,6812.7  ,249.5,246.2,242.6
XS GIS Cut Line= 4
     1864224.119      534171.402     1864274.467      534220.013
     1864394.258      534298.138     1864515.786      534346.749
#Sta/Elev= 30
       0  664.54    17.5  657.79    26.2  654.78    61.2  643.13      70  640.73
    79.5  638.95      89  638.17    98.6  637.46   108.1  637.04   117.7   636.8
   127.2  636.15   146.3  632.15   158.1  631.83   174.9  631.63   184.4  632.26
   193.9  635.12   203.5  638.96     213  643.66   222.4  647.26   231.7  649.98
     241  652.96   250.4  656.31   259.8  659.46   269.1  661.49   278.4  662.52
   287.8  663.99   297.1  666.34   306.5  669.43   325.2  675.93   343.9  683.83
#Mann= 3 , 0 , 0
       0      .1       0   158.1    .045       0   174.9      .1       0
Bank Sta=158.1,174.9
XS Rating Curve= 0 ,0
Exp/Cntr=0.3,0.1

Type RM Length L Ch R = 1 ,6566.5  ,193.9,194,194.2
XS GIS Cut Line= 3
     1864113.008      534369.318     1864205.022      534470.013
     1864397.731      534563.763
#Sta/Elev= 26
       0  643.05     9.7  639.23    19.5  636.99    29.2  636.51   107.2  636.23
   126.7  636.01   146.1  635.63   155.9  635.14   165.6  632.72   175.4  629.84
   185.1   629.2   194.8  629.62   204.6  631.55   214.3  634.34   224.1  636.47
   233.8  637.36   243.6  639.02   253.3  642.59     263  649.26   282.5   664.5
   292.3  671.83     302  678.36   311.7  683.61   321.5  688.81   331.2  693.48
   350.7  701.73
#Mann= 3 , 0 , 0
       0      .1       0   175.4    .045       0   194.8      .1       0
Bank Sta=175.4,194.8
XS Rating Curve= 0 ,0
Exp/Cntr=0.3,0.1

Type RM Length L Ch R = 1 ,6372.5  ,187.1,186.7,186.3
XS GIS Cut Line= 3
     1863958.494      534562.027     1864246.689      534704.388
      1864389.05      534740.846
#Sta/Elev= 30
       0  674.01     9.7  664.01    29.2  642.45      39  634.96    48.7  632.65
   107.2  631.65   185.1  632.61   214.3  632.49     224  632.19   233.8  630.84
   243.5  628.85   248.5  628.19   253.2  627.57     263  627.33   272.7  628.52
   282.5  633.69   292.2  636.67     302  637.55   311.7  639.05   321.4  644.41
     341  662.95   350.8  670.17   360.6  676.69   370.4  682.86   380.2  687.85
   409.6  700.27   429.2   709.7     439  715.57   448.8  722.92   468.4  738.28
#Mann= 3 , 0 , 0
       0      .1       0   248.5    .045       0   272.7      .1       0
Bank Sta=248.5,272.7
XS Rating Curve= 0 ,0
Exp/Cntr=0.3,0.1

Type RM Length L Ch R = 1 ,6185.8  ,305.8,324.8,342.8
XS GIS Cut Line= 6
     1863864.744      534692.235     1863899.467      534742.582
     1864182.453      534876.263     1864258.842      534890.152
     1864456.075      535393.329     1864915.613      535674.107
#Sta/Elev= 30
       0  686.95    17.5  678.15    52.4  643.88    70.9  631.22   119.8  628.31
   207.9  630.26   276.3   626.3   286.1  626.05     293  626.59   315.4  631.04
   374.1  636.09   393.5  639.82   432.4  651.03   451.8  661.45   461.6   663.1
     550  668.68   618.8  677.79   726.9  688.08   864.5  709.87   903.8  700.88
   952.9  694.12   992.2  684.14  1031.4  683.18  1080.4  686.71  1217.4   686.8
    1286  677.88  1344.7   657.1  1374.1  651.79  1491.6   653.7  1530.8  659.06
#Mann= 3 , 0 , 0
       0      .1       0   276.3    .045       0     293      .1       0
Bank Sta=276.3,293
XS Rating Curve= 0 ,0
Exp/Cntr=0.3,0.1