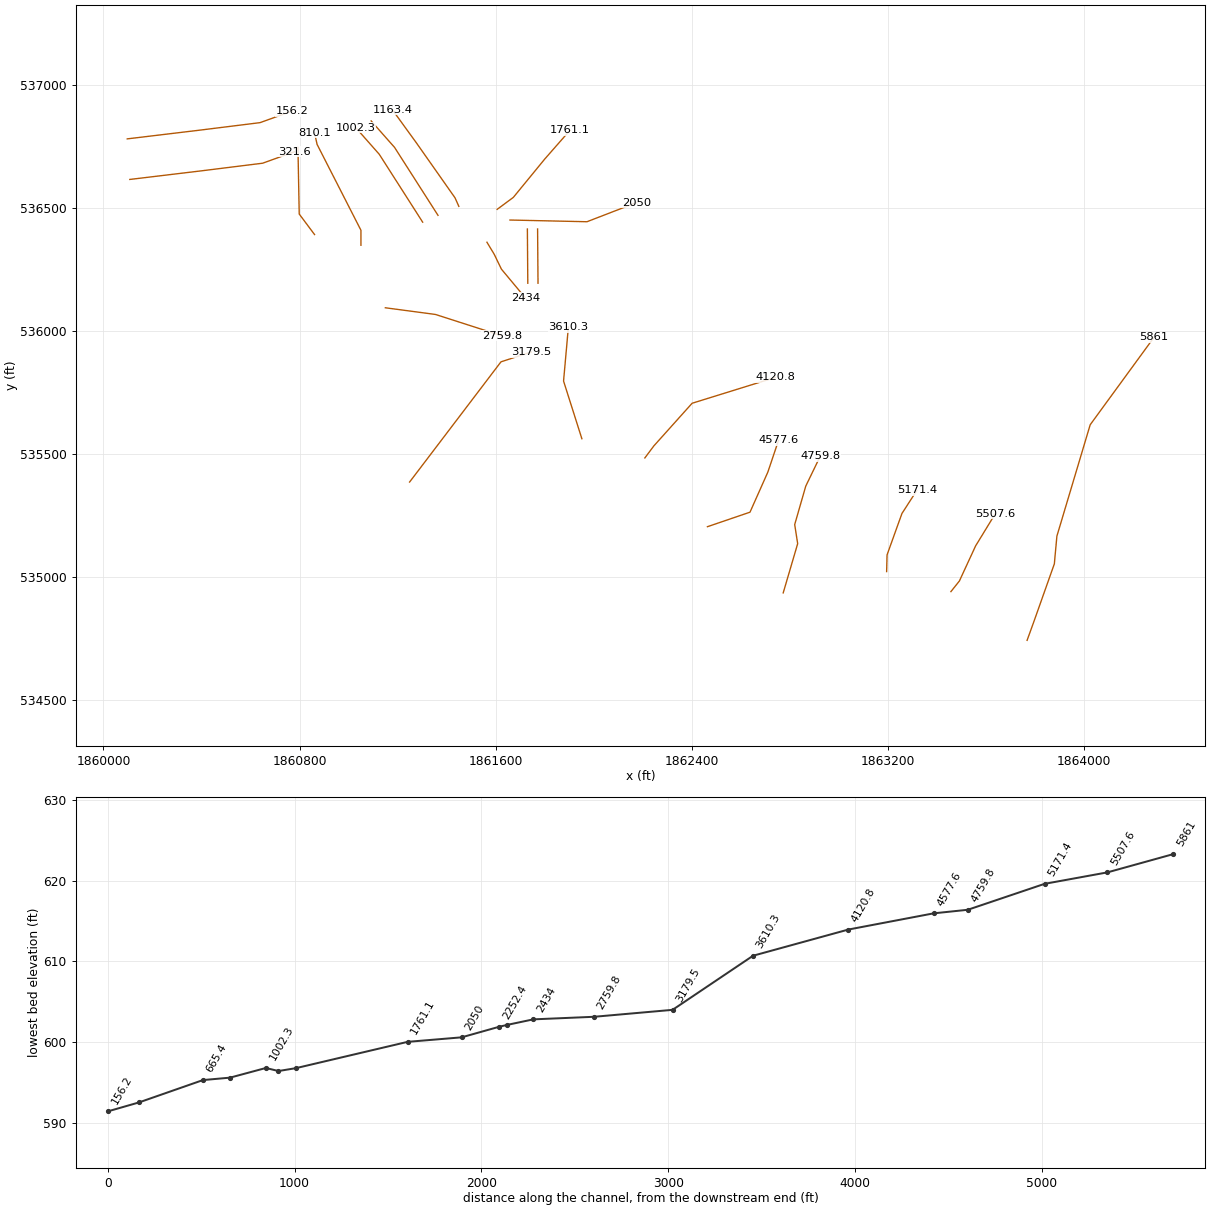
HEC-RAS study LEATHRWDFK.prj: LEATHRWDFK

--- LEATHRWDFK.g01 (geometry) --- (continued)

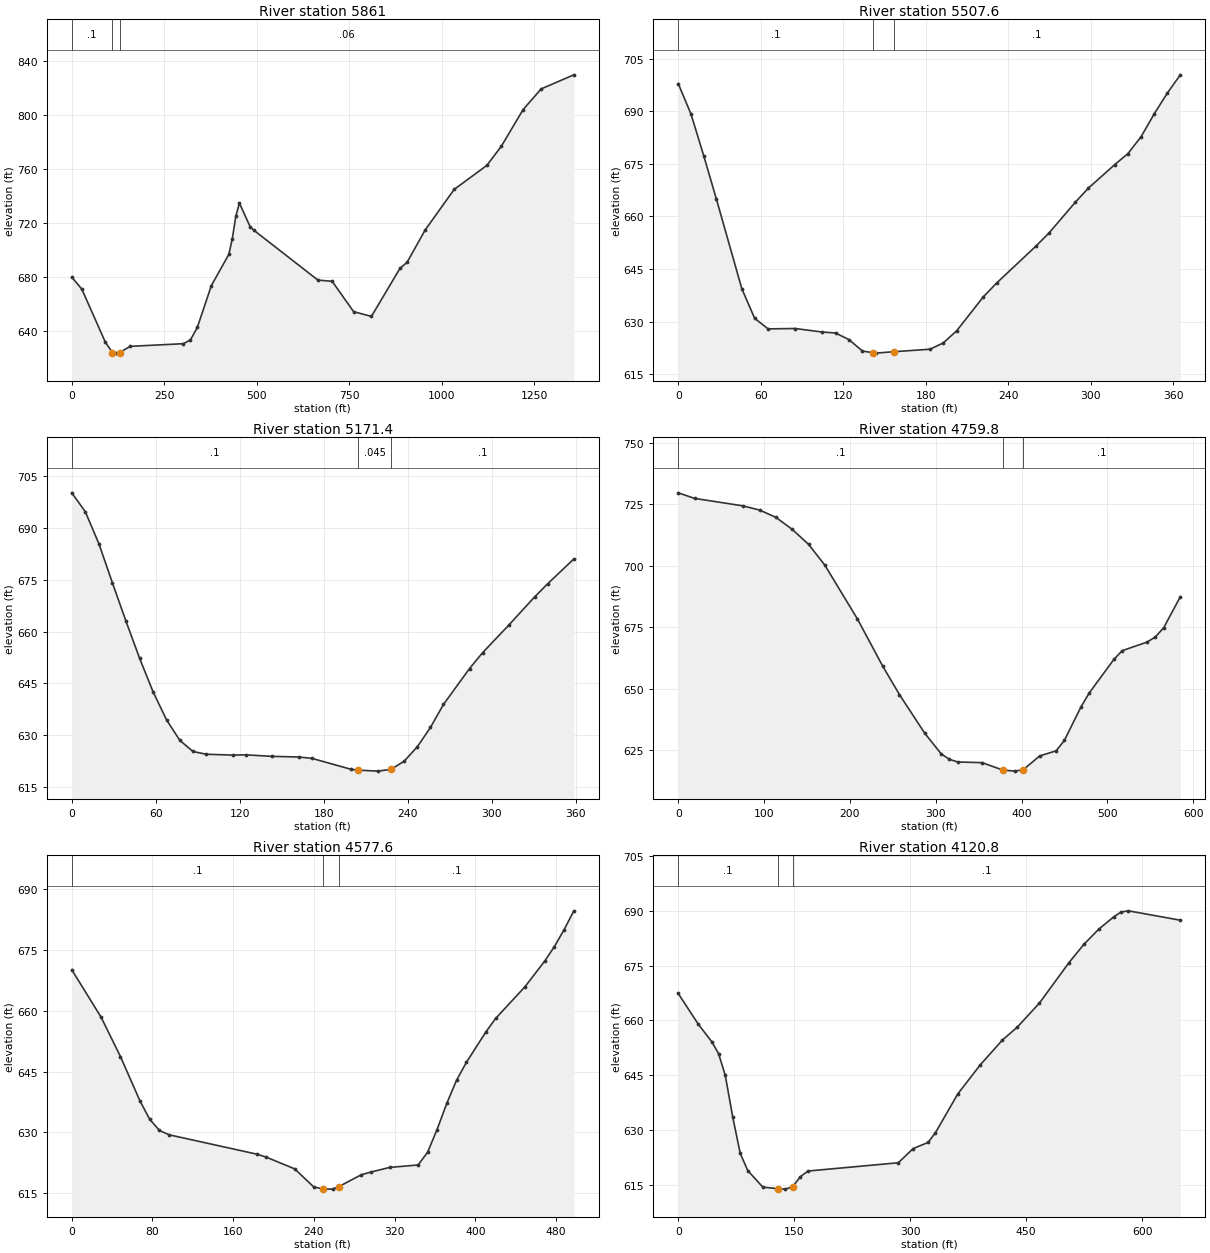
Type RM Length L Ch R = 1 ,5861    ,355.3,353.5,352
XS GIS Cut Line= 6
     1863767.522      534744.318       1863795.3      534820.707
     1863878.633      535055.082      1863889.05       535167.93
     1864024.824       535620.51     1864285.404      535976.191
#Sta/Elev= 30
       0  679.65    27.1   670.8    90.8  631.37     110  623.74   119.6  623.31
   129.1   623.7   157.8  628.34   301.3   630.3   320.5  632.98   339.5   642.5
   377.2   673.4   424.5  696.56   433.9   708.3   443.4  724.93     453  734.61
   481.9  717.12   491.6  714.54   665.2  677.46   703.7  676.58   761.6  654.08
   809.8  650.54   886.9  686.18   906.2  690.67   955.1  714.65  1033.4  744.72
  1121.6  762.49  1160.8   776.7  1219.6  803.87  1268.6  819.26  1356.8  829.68
#Mann= 3 , 0 , 0
       0      .1       0     110    .045       0   129.1     .06       0
Bank Sta=110,129.1
XS Rating Curve= 0 ,0
Exp/Cntr=0.3,0.1

Type RM Length L Ch R = 1 ,5507.6  ,334.4,336.2,336.9
XS GIS Cut Line= 4
     1863456.758      534942.235     1863491.481      534985.638
     1863557.453      535127.999     1863637.314      535258.207
#Sta/Elev= 30
       0  697.89     9.3  689.19    18.5  677.38    27.8   664.9    46.3  639.35
    55.6  630.95    65.4  627.95      85  628.06   104.6  627.06   114.4  626.78
   124.2  624.89     134  621.63     142  621.15   143.8  621.04     157  621.45
   183.1  622.15   192.9  623.97   202.7  627.49     222  637.12   231.6  641.03
   260.2  651.56   269.8  655.34   288.9   664.1   298.4  668.11   317.5  674.79
     327  677.89   336.6   682.7   346.1  689.18   355.7  695.16   365.2  700.39
#Mann= 3 , 0 , 0
       0      .1       0     142    .045       0     157      .1       0
Bank Sta=142,157
XS Rating Curve= 0 ,0
Exp/Cntr=0.3,0.1

Type RM Length L Ch R = 1 ,5171.4  ,409.9,411.6,413.4
XS GIS Cut Line= 4
     1863194.606      535023.832     1863196.342      535091.541
     1863257.106      535259.943     1863317.869      535353.693
#Sta/Elev= 30
       0  700.15     9.7  694.66    19.4  685.38      29  674.12    38.7  663.01
    48.4  652.32      58  642.62    67.7  634.44    77.2   628.5    86.6   625.3
      96  624.51   114.8  624.26   124.3  624.33   143.1  623.89     162  623.71
   171.4  623.32   199.6  620.13   204.6  619.91   218.5  619.62   227.9  620.12
   237.3  622.47   246.8  626.71   256.1  632.25   265.4  638.91     284   649.3
   293.3  653.87   311.9  661.81   330.6  670.08   339.9  673.86   358.5  681.02
#Mann= 3 , 0 , 0
       0      .1       0   204.6    .045       0   227.9      .1       0
Bank Sta=204.6,227.9
XS Rating Curve= 0 ,0
Exp/Cntr=0.3,0.1

Type RM Length L Ch R = 1 ,4759.8  ,185.3,182.2,179.1
XS GIS Cut Line= 5
     1862772.731      534937.027     1862831.775      535137.227
     1862819.606      535214.805     1862864.744      535371.055
     1862923.772      535492.582
#Sta/Elev= 30
       0  729.74      19  727.48    75.9   724.4    94.9  722.71   113.8  719.75
   132.8  714.86   151.8  708.78   170.8   700.3   208.7  678.42   238.2  659.18
   257.8  647.55   287.2  631.85   306.4  623.42     316  621.21   325.5  620.13
   354.2  619.85   378.1  616.83   392.5   616.4   402.1     617   421.2   622.6
   440.3  624.67   449.9  628.91   469.2  642.51   478.8  648.19   507.8     662
   517.4  665.48   546.4  668.96     556  671.06   565.7  674.84     585  687.42
#Mann= 3 , 0 , 0
       0      .1       0   378.1    .045       0   402.1      .1       0
Bank Sta=378.1,402.1
XS Rating Curve= 0 ,0
Exp/Cntr=0.3,0.1

Type RM Length L Ch R = 1 ,4577.6  ,463.2,456.8,449.8
XS GIS Cut Line= 4
     1862463.703      535206.124     1862637.314      535265.152
     1862710.231      535428.346     1862753.633      535556.818
#Sta/Elev= 30
       0  670.14      29  658.46    48.3  648.68    67.6  637.76    77.2  633.23
    86.9  630.45    96.5  629.38   183.4   624.6   192.8  623.86     221  620.96
   239.8  616.51   249.2  615.99   258.6  615.96   264.9   616.6   286.8  619.49
   296.3  620.16   315.1  621.32   343.3  621.93   352.7  625.06   362.1  630.68
   371.8  637.17   381.5   642.9   391.2  647.28   410.6  654.82   420.2  658.13
   449.3  665.96   468.7  672.24   478.4  675.86     488  680.03   497.7   684.7
#Mann= 3 , 0 , 0
       0      .1       0   249.2    .045       0   264.9      .1       0
Bank Sta=249.2,264.9
XS Rating Curve= 0 ,0
Exp/Cntr=0.3,0.1

Type RM Length L Ch R = 1 ,4120.8  ,485.4,510.6,535.2
XS GIS Cut Line= 4
     1862208.494      535485.638     1862244.953      535534.249
     1862401.203       535707.86     1862740.335      535812.736
#Sta/Elev= 30
       0  667.37      26  658.96    43.4  654.19    52.1  650.98    60.8  645.04
    70.5  633.58    80.2  623.69      90  618.99   109.4  614.49   128.9  614.08
   138.6  613.95   147.9   614.6   158.1  617.38   167.8  618.89   284.6  621.15
   303.9  625.04   323.1  626.69   332.7  629.38   361.5  639.94   390.3  647.81
   419.1  654.63   438.2  658.13     467  664.72   505.4  675.82   524.6  680.78
   543.8  684.93     563  688.26   572.6  689.61   582.2  689.94   649.3  687.38
#Mann= 3 , 0 , 0
       0      .1       0   128.9    .045       0   147.9      .1       0
Bank Sta=128.9,147.9
XS Rating Curve= 0 ,0
Exp/Cntr=0.3,0.1

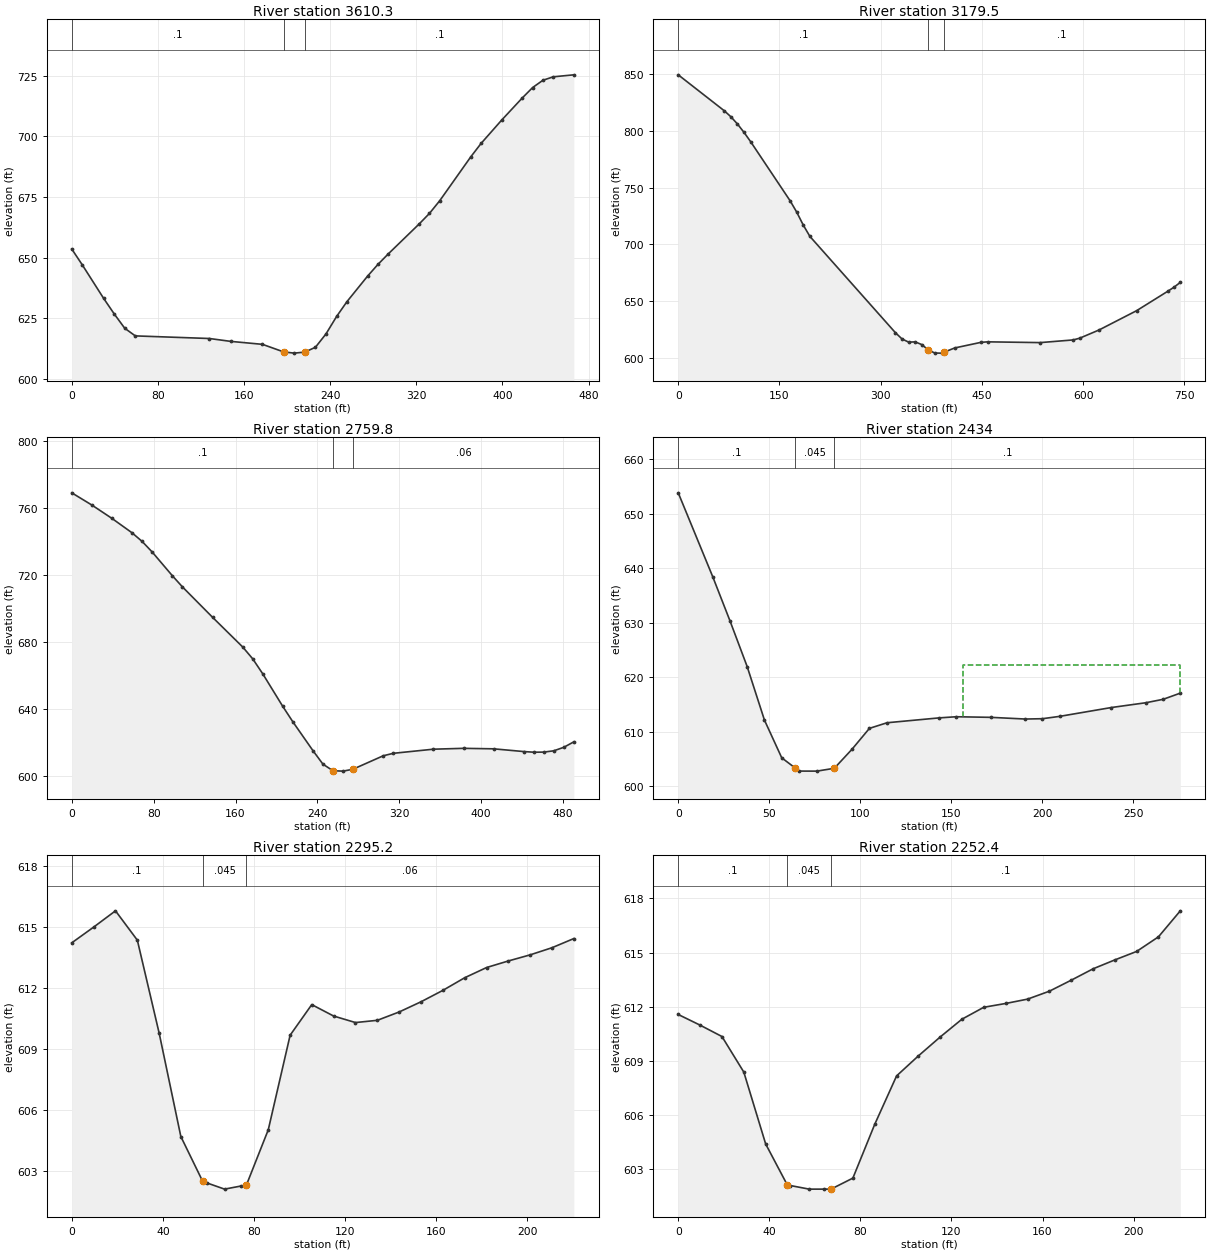
Type RM Length L Ch R = 1 ,3610.3  ,452.9,430.7,408.7
XS GIS Cut Line= 3
      1861951.55      535563.763     1861876.897      535798.138
     1861896.585      536017.597
#Sta/Elev= 30
       0  653.58     9.8  647.03    29.5  633.32    39.4  626.86    49.2  620.94
      59   617.8   127.9  616.72   147.6  615.54   177.1  614.32   196.8   611.2
   206.6   610.7   216.4  611.12   226.3  613.11   236.1  618.61     246  625.83
   255.6  631.92   274.7   642.4   284.3  647.22   293.9  651.55   322.6  663.88
   332.2  668.25   341.8  673.51   370.5   691.5   380.1  697.05   399.3   706.7
   418.4   715.8     428  720.08   437.6   723.1   447.2  724.51   466.3  725.33
#Mann= 3 , 0 , 0
       0      .1       0   196.8    .045       0   216.4      .1       0
Bank Sta=196.8,216.4
XS Rating Curve= 0 ,0
Exp/Cntr=0.3,0.1

Type RM Length L Ch R = 1 ,3179.5  ,447.7,419.7,391.8
XS GIS Cut Line= 3
     1861248.946      535387.649     1861621.689      535876.263
     1861744.953      535916.193
#Sta/Elev= 30
       0   849.6    68.3  817.85      78  812.61    87.8  806.18    97.6  798.72
   107.3  790.61   165.8  738.45   175.6  728.43   185.3  717.01   195.1  707.01
   321.9     622   331.7  616.48   341.4  613.71   351.2  613.91   360.9  611.54
   370.7   606.8   380.4  604.04   390.2  603.99   393.8  604.77   409.7  608.55
   448.7  613.51   458.5  613.96   536.5  613.28   585.3  615.64     595  617.18
   623.8  624.46   679.3  641.44   725.6  658.62   734.9  662.23   744.1  666.45
#Mann= 3 , 0 , 0
       0      .1       0   370.7    .045       0   393.8      .1       0
Bank Sta=370.7,393.8
XS Rating Curve= 0 ,0
Exp/Cntr=0.3,0.1

Type RM Length L Ch R = 1 ,2759.8  ,343.4,325.8,307.5
XS GIS Cut Line= 3
     1861149.988      536095.982     1861354.434      536068.859
     1861625.161      535982.166
#Sta/Elev= 30
       0   769.2    19.6  761.92    39.3  753.92    58.9  745.34    68.8  740.16
    78.6  733.86    98.2  719.78     108  713.14   137.5  694.95     167   677.2
   176.8  670.12   186.6  661.18   206.2   641.7     216  632.54   235.6  615.37
   245.4  607.28   255.2  603.35     265  603.13   274.6  604.23   304.3  612.29
   314.1  613.76   353.3  616.22   382.7  616.73   412.1  616.44   441.5  614.81
   451.3  614.42   461.1  614.48   470.9  615.26   480.7  617.35   490.5  620.61
#Mann= 3 , 0 , 0
       0      .1       0   255.2    .045       0   274.6     .06       0
Bank Sta=255.2,274.6
XS Rating Curve= 0 ,0
Exp/Cntr=0.3,0.1

Type RM Length L Ch R = 1 ,2434    ,149.6,138.8,128.6
XS GIS Cut Line= 4
     1861564.397      536362.374     1861593.911      536313.763
     1861623.425      536252.999     1861720.647       536136.68
#Sta/Elev= 23
       0  653.83      19  638.42    28.4   630.4    37.9  621.97    47.4  612.16
    56.9  605.25    64.3  603.38    66.5  602.82    76.2  602.81    85.8  603.33
    95.5  606.81   105.1  610.65   114.8  611.68   143.4  612.57   152.8  612.78
   171.8  612.67   190.8  612.36   200.2  612.42   209.7  612.85   238.1  614.47
   257.1  615.35   266.6  615.98     276  617.11
#Mann= 3 , 0 , 0
       0      .1       0    64.3    .045       0    85.8      .1       0
#XS Ineff= 2 , 0
                          156.78          622.35
Permanent Ineff=
       F       F
Bank Sta=64.3,85.8
XS Rating Curve= 0 ,0
Exp/Cntr=0.3,0.1

Type RM Length L Ch R = 1 ,2295.2  ,42.8,42.8,43
XS GIS Cut Line= 2
     1861729.328      536416.193     1861731.064      536195.707
#Sta/Elev= 26
       0  614.21     9.6  614.98    19.2  615.78    28.8  614.34    38.4  609.77
    47.9  604.71    57.5  602.51    59.2  602.44    67.1  602.13    74.2  602.28
    76.7  602.33    86.3  605.04    95.9  609.68   105.4  611.18     115  610.62
   124.6   610.3   134.2  610.41   143.8  610.82   153.4  611.32     163  611.88
   172.6   612.5   182.2     613   191.7  613.32   201.3  613.62   210.9  613.97
   220.5  614.42
#Mann= 3 , 0 , 0
       0      .1       0    57.5    .045       0    76.7     .06       0
Bank Sta=57.5,76.7
XS Rating Curve= 0 ,0
Exp/Cntr=0.3,0.1

Type RM Length L Ch R = 1 ,2252.4  ,166.6,202.4,238
XS GIS Cut Line= 2
     1861770.994      536416.193     1861772.731      536195.707
#Sta/Elev= 26
       0  611.57     9.6  610.98    19.2  610.35    28.8  608.38    38.4   604.4
    47.9  602.13    49.2   602.1    57.5   601.9    64.2   601.9    67.1   601.9
    76.7  602.51    86.3  605.49    95.9  608.17   105.4  609.27     115  610.32
   124.6  611.31   134.2  611.97   143.8  612.18   153.4  612.42     163  612.86
   172.6  613.47   182.2   614.1   191.7  614.59   201.3  615.06   210.9  615.87
   220.5  617.31
#Mann= 3 , 0 , 0
       0      .1       0    47.9    .045       0    67.1      .1       0
Bank Sta=47.9,67.1
XS Rating Curve= 0 ,0
Exp/Cntr=0.3,0.1

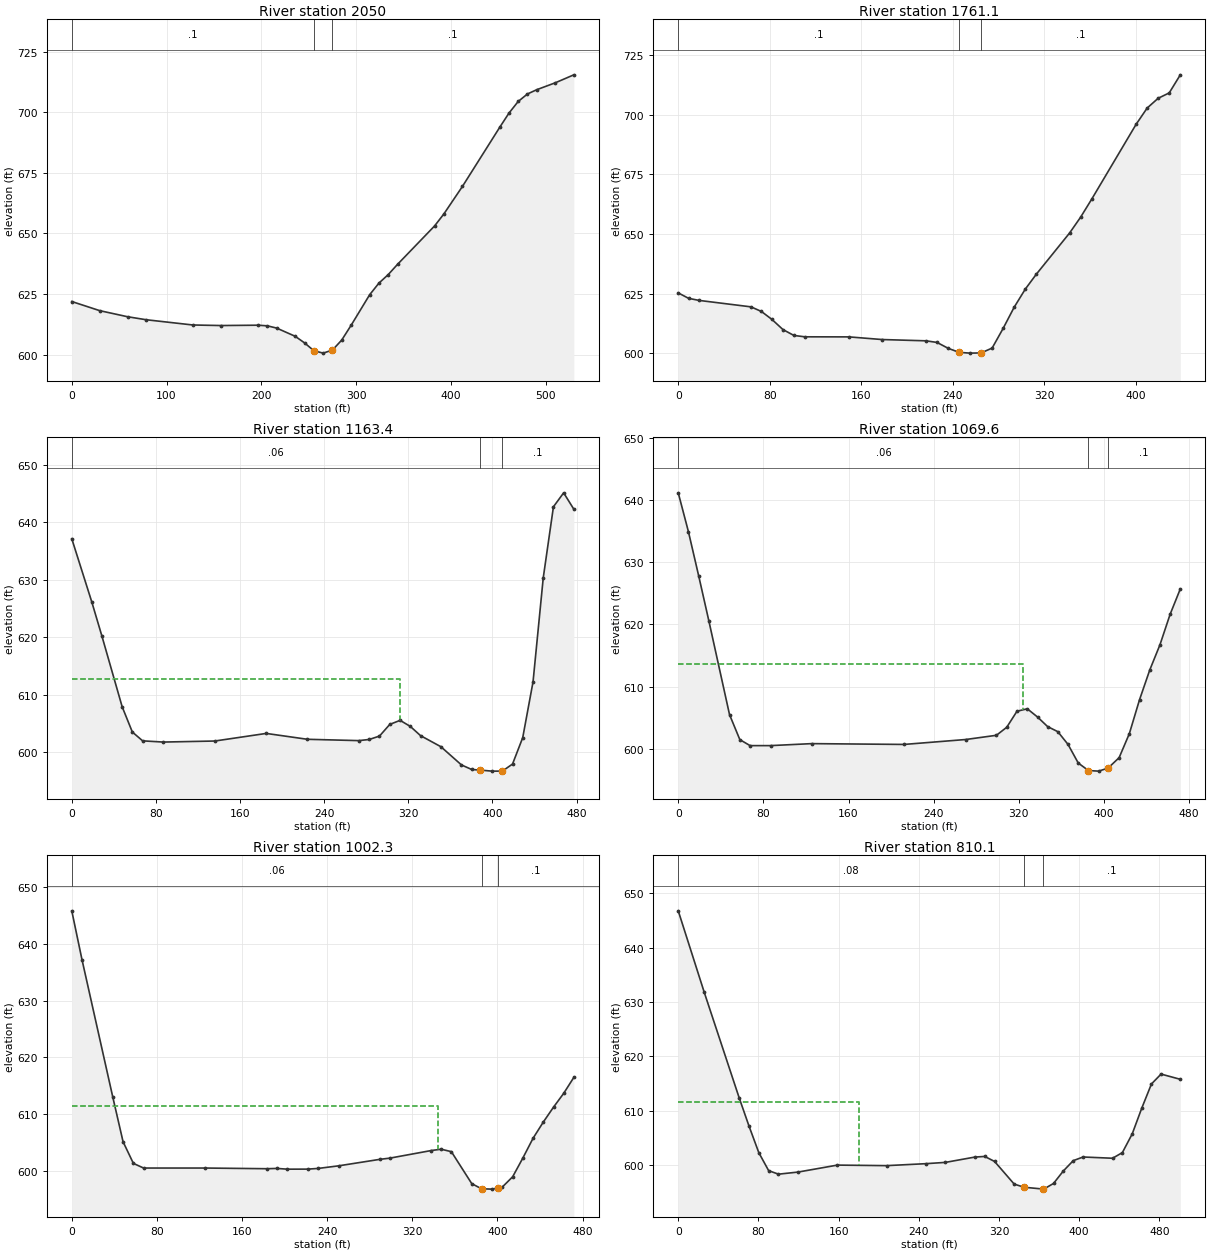
Type RM Length L Ch R = 1 ,2050    ,268.5,289,309.4
XS GIS Cut Line= 3
     1861658.147      536452.652     1861972.383      536445.707
     1862173.425      536523.066
#Sta/Elev= 30
       0  621.87    29.5   618.1    58.9  615.59    78.6  614.35   127.7  612.19
   157.2  611.96   196.4   612.1   206.3  611.84   216.1  610.92   235.7  607.53
   245.6   604.8   255.4  601.58   265.2  600.58     275  601.84   284.8  605.96
   294.7  612.05   314.3  624.68   324.1  629.48   333.9  632.99   343.7  637.21
   382.8  653.06   392.6  658.01   412.2  669.38   451.4  693.68   461.2  699.57
     471  704.41   480.8   707.5   490.6  709.26   510.1   712.1   529.7  715.39
#Mann= 3 , 0 , 0
       0      .1       0   255.4    .045       0     275      .1       0
Bank Sta=255.4,275
XS Rating Curve= 0 ,0
Exp/Cntr=0.3,0.1

Type RM Length L Ch R = 1 ,1761.1  ,566.3,597.7,629.1
XS GIS Cut Line= 4
     1861606.064      536496.055     1861672.036      536544.666
     1861800.508      536700.916     1861902.939      536817.235
#Sta/Elev= 30
       0  625.28     9.1  622.99    18.2  622.13    63.7  619.42    72.8  617.48
      82  614.14    91.6   609.9   101.2  607.43   110.8  606.86   149.4  606.83
   178.3  605.72   216.8  605.18   226.4   604.5   236.1  602.05   245.7  600.34
   255.3  600.02     265  600.11   274.6  602.15   284.2  610.38   293.9   619.3
   303.6  626.87   313.3  633.15   342.4  650.43     352  657.04   361.7   664.6
   400.5  695.95   410.2   702.8   419.8  706.89   429.5  709.15   439.2  716.73
#Mann= 3 , 0 , 0
       0      .1       0   245.7    .045       0     265      .1       0
Bank Sta=245.7,265
XS Rating Curve= 0 ,0
Exp/Cntr=0.3,0.1

Type RM Length L Ch R = 1 ,1163.4  ,93,93.8,94.7
XS GIS Cut Line= 4
     1861449.814      536508.207     1861434.189       536542.93
     1861276.203      536766.888     1861178.981      536900.568
#Sta/Elev= 30
       0  637.14      19  626.17    28.6  620.26    47.9  607.95    57.6  603.55
    67.4  602.02      87  601.81     136  601.99   184.9  603.31   224.1  602.29
     273  602.06   282.8  602.26   292.6  602.85   302.4  604.88   312.2  605.58
   321.9  604.53   331.6  602.93     351     601   370.5  597.84   380.2  597.05
   388.6  596.93   399.7  596.76   409.4  596.76   419.1  597.99   428.8  602.58
   438.6  612.27   448.3  630.33     458  642.69   467.7  645.11   477.4  642.26
#Mann= 3 , 0 , 0
       0     .06       0   388.6    .045       0   409.4      .1       0
#XS Ineff= 2 , 0
          311.78  612.73
Permanent Ineff=
       F       F
Bank Sta=388.6,409.4
XS Rating Curve= 0 ,0
Exp/Cntr=0.3,0.1

Type RM Length L Ch R = 1 ,1069.6  ,67.6,67.3,67.6
XS GIS Cut Line= 3
     1861364.744      536471.749     1861187.661      536747.791
     1861092.175       536855.43
#Sta/Elev= 30
       0  641.13     9.6  634.87    19.3  627.72    28.9  620.45    48.2  605.48
    57.9  601.46    67.5   600.5    86.8   600.5   125.4  600.82   212.2  600.69
   270.1  601.48     299  602.16   308.7  603.45   318.3  606.02     328  606.42
   337.6   605.1   347.1  603.56   356.7  602.74   366.3  600.69   375.9   597.7
   385.5  596.49   395.1   596.4   403.9  596.89   414.3  598.56   423.9  602.42
   433.5  607.89   443.1  612.66   452.7  616.72   462.2   621.6   471.8  625.69
#Mann= 3 , 0 , 0
       0     .06       0   385.5    .045       0   403.9      .1       0
#XS Ineff= 2 , 0
          323.74  613.57
Permanent Ineff=
       F       F
Bank Sta=385.5,403.9
XS Rating Curve= 0 ,0
Exp/Cntr=0.3,0.1

Type RM Length L Ch R = 1 ,1002.3  ,197.7,192.2,186
XS GIS Cut Line= 3
     1861302.244      536443.971     1861125.161      536720.013
     1861029.675      536827.652
#Sta/Elev= 30
       0  645.87     9.6  637.26    38.6  612.97    48.2  605.14    57.9  601.32
    67.5   600.5   125.4   600.5   183.3  600.38   192.9  600.43   202.6   600.3
   221.9  600.31   231.5  600.43   250.8  600.89   289.4  602.03     299  602.25
   337.6  603.58   347.1  603.82   356.7  603.39   375.9  597.74   385.1  596.84
   395.1  596.78   400.1  596.98   404.7  597.17   414.3  598.96   423.9  602.27
   433.5  605.76   443.1  608.61   452.7  611.24   462.2  613.66   471.8  616.49
#Mann= 3 , 0 , 0
       0     .06       0   385.1    .045       0   400.1      .1       0
#XS Ineff= 2 , 0
          344.11  611.43
Permanent Ineff=
       F       F
Bank Sta=385.1,400.1
XS Rating Curve= 0 ,0
Exp/Cntr=0.3,0.1

Type RM Length L Ch R = 1 ,810.1   ,156.5,144.7,132.9
XS GIS Cut Line= 4
     1861050.508      536350.221     1861050.508      536410.985
     1860871.689      536759.943     1860861.272      536806.818
#Sta/Elev= 30
       0  646.77      26  631.75    60.8  612.37    70.6  607.18    80.4  602.28
    90.2  598.98     100  598.33   119.6  598.72   158.8     600   207.8   599.9
     247  600.26   266.6   600.5     296  601.48   305.8  601.59   315.6  600.67
   335.2   596.5     345  595.93   363.6   595.6   364.6  595.58   374.4  596.62
   384.2  598.92   394.1  600.82   403.9  601.49   433.3  601.26   443.1   602.3
   452.9  605.73   462.5   610.5   472.1  614.92   481.7  616.74   500.9  615.78
#Mann= 3 , 0 , 0
       0     .08       0     345    .045       0   363.6      .1       0
#XS Ineff= 2 , 0
          180.16  611.58
Permanent Ineff=
       F       F
Bank Sta=345,363.6
XS Rating Curve= 0 ,0
Exp/Cntr=0.3,0.1

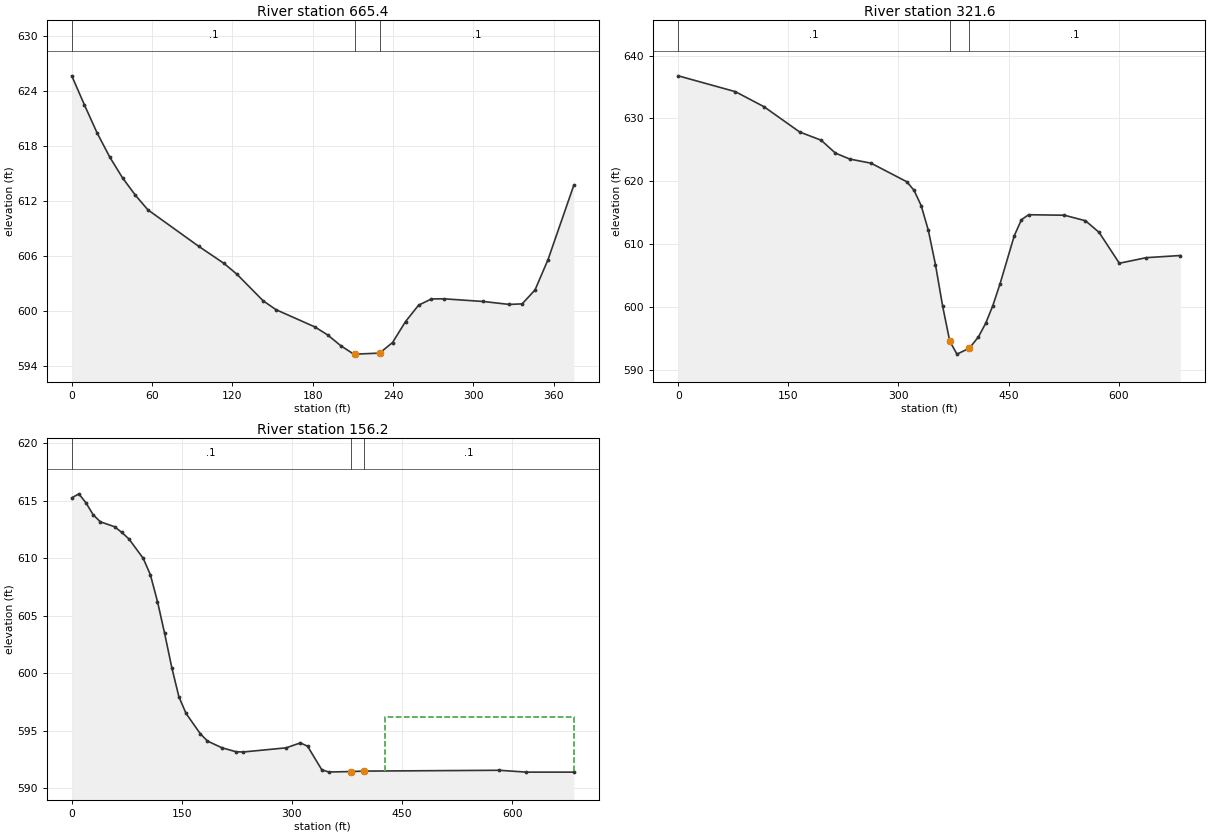
Type RM Length L Ch R = 1 ,665.4   ,376.4,343.7,309.9
XS GIS Cut Line= 3
     1860861.272      536393.624     1860798.772      536476.957
     1860793.564      536747.791
#Sta/Elev= 29
       0  625.68     9.5  622.49    18.9  619.45    28.4   616.8    37.9  614.54
    47.4  612.66    56.8  611.05    94.7  607.07   113.8  605.18   123.5  603.99
   142.9  601.11   152.5  600.14   181.6  598.25   191.2  597.37   200.9   596.2
   210.6  595.28   211.6  595.28   229.9  595.39   239.6  596.55   249.3  598.84
     259  600.62   268.6  601.31   278.3  601.32   307.3  601.03   326.7  600.71
   336.4  600.77     346  602.29   355.7   605.6     375  613.74
#Mann= 3 , 0 , 0
       0      .1       0   211.6    .045       0   229.9      .1       0
Bank Sta=211.6,229.9
XS Rating Curve= 0 ,0
Exp/Cntr=0.3,0.1

Type RM Length L Ch R = 1 ,321.6   ,165.4,165.4,166.6
XS GIS Cut Line= 4
       1860107.8      536617.582     1860397.731      536652.305
     1860649.467      536683.555     1860779.675       536730.43
#Sta/Elev= 30
       0  636.78    77.9  634.26   116.8  631.87   165.5  627.84   194.7  626.54
   214.1  624.49   233.6  623.54   262.8  622.88   311.5  619.92   321.3  618.56
     331  616.14   340.8  612.19   350.5  606.73   360.3  600.11     370  594.54
   379.8   592.5   396.7  593.44   409.1  595.26   418.8  597.38   428.6   600.2
   438.4  603.66   457.9  611.35   467.6  613.88   477.4  614.68   526.2   614.6
   554.9  613.72   573.4  611.88     601  606.96   637.9  607.85   684.1  608.19
#Mann= 3 , 0 , 0
       0      .1       0     370    .045       0   396.7      .1       0
Bank Sta=370,396.7
XS Rating Curve= 0 ,0
Exp/Cntr=0.3,0.1

Type RM Length L Ch R = 1 ,156.2   ,157.9,156.2,154.5
XS GIS Cut Line= 4
     1860097.383      536782.513     1860387.314      536817.235
      1860639.05      536848.485     1860769.258       536895.36
#Sta/Elev= 30
       0  615.23     9.7  615.58    19.5  614.78    29.2  613.76    38.9  613.15
    58.4  612.72    68.1  612.23    77.9  611.66    97.3  609.98   107.1  608.55
   116.8  606.22   126.5  603.46   136.3  600.48     146  597.94   155.7   596.5
   175.2  594.73   184.9   594.1   204.4  593.52   223.9  593.17   233.6  593.15
     292  593.51   311.5  593.94   321.3  593.65   340.8  591.59   350.5  591.41
   379.8  591.45   398.7  591.49   582.6  591.56   619.5   591.4   684.1   591.4
#Mann= 3 , 0 , 0
       0      .1       0   379.8    .045       0   398.7      .1       0
#XS Ineff= 2 , 0
                          427.19          596.16
Permanent Ineff=
       F       F
Bank Sta=379.8,398.7
XS Rating Curve= 0 ,0
Exp/Cntr=0.3,0.1

Chan Stop Cuts=-1
Use User Specified Reach Order=0
Composite Channel Slope=5